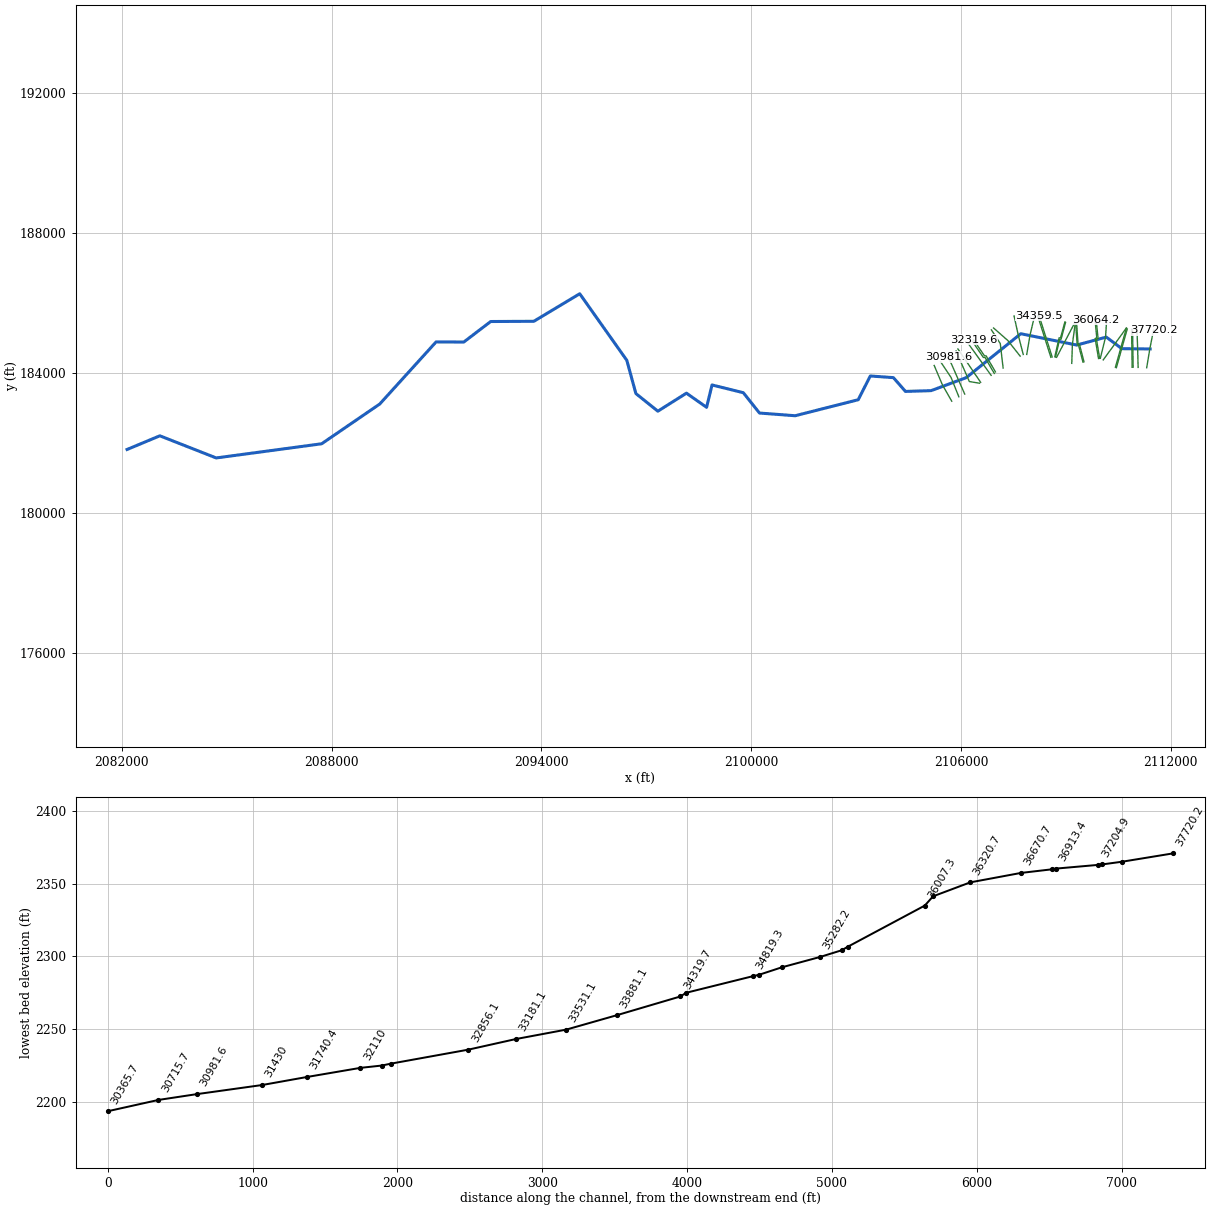
--- DRPLKCR.prj (project) ---

Proj Title=DRPLKCR
Current Plan=p01
Default Exp/Contr=0,0
English Units
Geom File=g01
Flow File=f01
Plan File=p01
BEGIN DESCRIPTION:
END DESCRIPTION:
DSS Export Rating Curves= 0
DSS Export Rating Curve Sorted= 0
DSS Export Volume Flow Curves= 0
DXF OffsetX= 0
DXF OffsetY= 0
DXF ScaleX= 0
DXF ScaleY= 0

--- DRPLKCR.p01 (plan) ---

Plan Title=Floodplain
Program Version=4.00
Geom File=g01
Flow File=f01
K Sum by GR=0
Std Step Tol=0.01
Critical Tol=0.01
Num of Std Step Trials=20
Max Error Tol=0.3
Flow Tol Ratio=0.001
Split Flow NTrial=30
Split Flow Tol=0.02
Split Flow Ratio=0.02
Log Output Level=0
Friction Slope Method=1
Unsteady Friction Slope Method=2
Unsteady Bridges Friction Slope Method=1
Global Log Level=0
CheckData=False
Run HTab=0
Run UNet=0
Run PostProcess=0
UNET Theta=0
UNET Theta Warmup=0
UNET ZTol=0
UNET ZSATol=0
UNET MxIter=0
UNET MaxInSteps=0
UNET DtIC=0
UNET DtMin=0
UNET MaxCRTS=0
UNET WFStab=0
UNET SFStab=0
UNET WFX=0
UNET SFX=0
UNET DSS MLevel=0
UNET DZMax Abort=0
UNET Convert EG Bridges=0
UNET Use Existing IB Tables=0
UNET Froude Limit=0
UNET Froude Power=0
Write IC File=0
Echo Input=False
Echo Output=False
Write Detailed=0

--- DRPLKCR.f01 (steady flow) ---

Flow Title=2010 USGS WV Regression Equation
Program Version=4.00
Number of Profiles=1
Profile Names=P100yr
River Rch & RM=DRPLKCR,Main      ,37720.2
549.8185
River Rch & RM=DRPLKCR,Main      ,36064.2
572.6439
River Rch & RM=DRPLKCR,Main      ,33881.1
625.6383
River Rch & RM=DRPLKCR,Main      ,30981.6
692.0696
River Rch & RM=DRPLKCR,Main      ,30715.7
1016.690
River Rch & RM=DRPLKCR,Main      ,28270.4
1047.403
River Rch & RM=DRPLKCR,Main      ,27867.4
1273.282
River Rch & RM=DRPLKCR,Main      ,23369.7
1351.582
River Rch & RM=DRPLKCR,Main      ,23019.7
1618.554
River Rch & RM=DRPLKCR,Main      ,19518.8
1791.783
River Rch & RM=DRPLKCR,Main      ,12862.8
1915.697
River Rch & RM=DRPLKCR,Main      ,8197.2
2126.054
River Rch & RM=DRPLKCR,Main      ,845.3
2324.038
River Rch & RM=DRPLKCR,Main      ,285.2
2328.317
Boundary for River Rch & Prof#=DRPLKCR,Main      ,1
Up Type=0
Dn Type=3
Dn Slope=0.006067

--- DRPLKCR.g01 (geometry) ---

Geom Title=LiDAR
Program Version=4.10

River Reach=DRPLKCR         ,Main
Reach XY= 30
     2111411.299      184687.778     2110603.072      184694.653
     2110156.812      185026.491      2109312.02      184798.886
     2107711.112      185122.775     2106150.746      183867.535
     2105145.574      183495.678     2104412.935      183473.977
     2104067.449       183867.64     2103406.858      183914.949
     2103061.806       183236.13       2101258.2      182778.856
     2100237.587      182855.487     2099774.827      183436.824
      2098880.73      183658.178      2098724.48      183019.289
     2098148.344      183423.747     2097330.506      182908.837
     2096702.584      183412.446     2096442.362      184363.039
     2095096.008      186264.949     2093784.376      185478.491
     2092549.133      185471.546     2091780.036      184885.175
      2090987.24      184888.647     2089376.129      183113.473
     2087714.671      181977.189     2084698.276      181572.206
     2083086.297      182205.019     2082150.195      181814.726

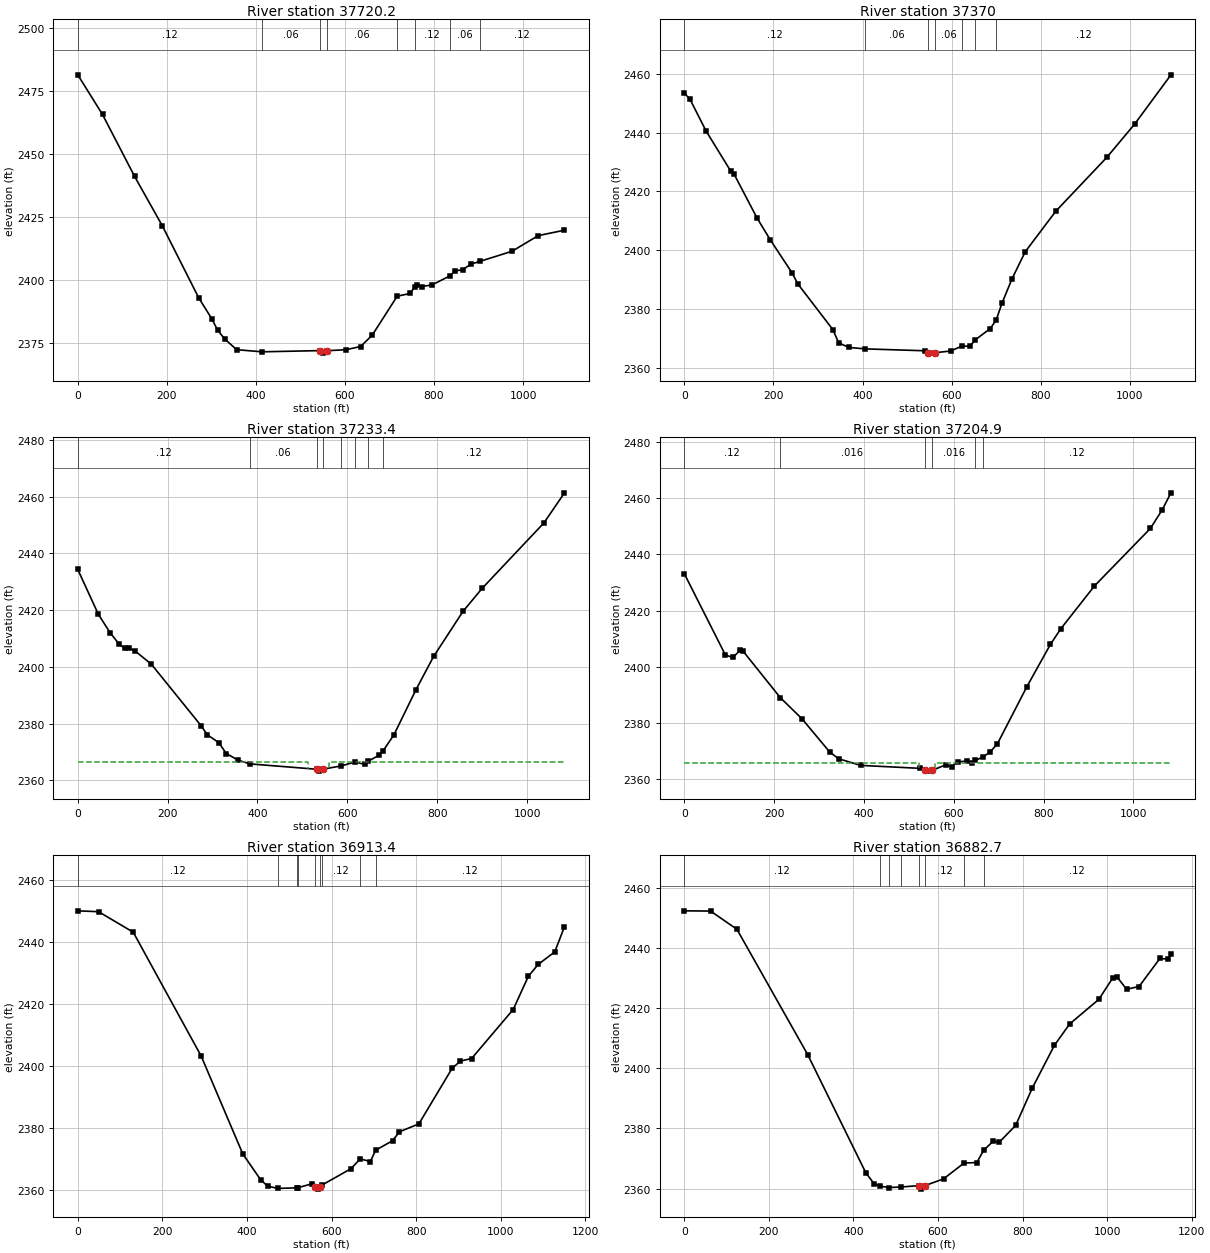
Type RM Length L Ch R = 1 ,37720.2 ,345.7,350.2,355.1
XS GIS Cut Line= 3
     2111312.755      184151.107     2111401.813      184690.524
     2111508.004      185226.332
#Sta/Elev= 30
       0 2481.48    55.6  2465.7   127.7 2441.05   189.9 2421.43   271.7 2392.75
   301.2 2384.39   314.3 2379.82   330.6 2376.32   356.8 2372.15  413.532371.304
   543.4 2371.78     550 2370.78  558.772371.735   602.3 2372.14     635 2373.41
   661.2  2377.9   717.32393.412   746.2 2394.51  756.912397.134   762.6 2397.98
   772.4 2397.28   795.3 2397.89   834.92401.447   847.6 2403.49     864 2403.95
   883.6 2406.22  903.412407.291   975.2  2411.3  1034.1 2417.53    1093 2419.68
#Mann= 8 ,-1 , 0
       0     .12       0  413.53     .06       0   543.4    .045       0
  558.77     .06       0   717.3    .016       0  756.91     .12       0
   834.9     .06       0  903.41     .12       0
Bank Sta=543.4,558.77
XS Rating Curve= 0 ,0
Exp/Cntr=0.3,0.1

Type RM Length L Ch R = 1 ,37370   ,136.9,136.6,136.1
XS GIS Cut Line= 3
       2111067.4      184160.193     2111053.461      184705.996
     2111034.263      185251.702
#Sta/Elev= 30
       0 2453.44    13.1 2451.28      49 2440.54   104.6 2426.86   111.2 2426.07
   163.5 2410.94   192.9 2403.61   241.9 2392.36     255 2388.57   333.5 2373.06
   346.6 2368.56   369.4 2367.02  405.052366.529   539.4 2365.88  547.992365.193
   549.2 2365.08   562.3  2365.2   598.3 2365.82  623.672367.534   640.8 2367.34
  651.942369.473   686.6 2373.42  699.922376.331   712.7 2381.96   735.6 2390.39
     765  2399.5   833.7  2413.3   948.2  2431.6  1010.3 2442.84    1092 2459.62
#Mann= 7 ,-1 , 0
       0     .12       0  405.05     .06       0  547.99    .045       0
   562.3     .06       0  623.67    .016       0  651.94     .06       0
  699.92     .12       0
Bank Sta=547.99,562.3
XS Rating Curve= 0 ,0
Exp/Cntr=0.3,0.1

Type RM Length L Ch R = 1 ,37233.4 ,28.5,28.5,28.5
XS GIS Cut Line= 2
     2110924.719      184165.855     2110909.094      185249.188
#Sta/Elev= 30
       0 2434.32    45.8 2418.52      72 2412.01    91.6  2408.1   104.7 2406.46
   114.6 2406.53   127.7 2405.56   163.7 2400.94     275 2379.14     288  2376.1
   314.2 2373.22   330.6 2369.44   356.8  2367.1     383 2365.78   531.5  2363.9
   536.8 2363.23  544.932363.903  587.012365.083  616.562366.431   638.3 2365.68
   646.12366.693     671 2368.85  679.752370.414   703.8 2376.04   752.8 2391.92
   792.1 2403.65   857.6 2419.55   900.1 2427.65  1037.6 2450.71  1083.4 2461.32
#Mann= 8 ,-1 , 0
       0     .12       0     383     .06       0   531.5    .045       0
  544.93     .06       0  587.01     .12       0  616.56    .016       0
   646.1     .06       0  679.75     .12       0
#XS Ineff= 2 , 0
          513.11 2366.28  558.12         2366.33
Permanent Ineff=
       F       F
Bank Sta=531.5,544.93
XS Rating Curve= 0 ,0
Exp/Cntr=0.3,0.1

Type RM Length L Ch R = 1 ,37204.9 ,297.9,291.5,284.9
XS GIS Cut Line= 2
     2110896.247      184163.772     2110880.622      185247.105
#Sta/Elev= 30
       0 2433.17    91.6 2404.21     108 2403.32   124.4 2405.85   130.9 2405.58
  213.862389.035   261.9 2381.55     324 2369.66   343.7  2367.3   392.8 2364.94
   523.7  2363.9  535.252363.177   540.1  2362.9     5512363.127   582.6 2365.17
   595.7 2364.43   608.8 2366.19   628.5 2366.46   641.6 2365.77  648.182366.692
  665.922368.022   680.8 2369.67   697.2 2372.65   762.7 2392.93     815 2407.94
     838 2413.48   913.2 2428.76  1037.6 2449.19  1063.8 2455.78  1083.4 2461.86
#Mann= 6 ,-1 , 0
       0     .12       0  213.86    .016       0  535.25    .045       0
     551    .016       0  648.18     .06       0  665.92     .12       0
#XS Ineff= 2 , 0
          523.22  2365.7  559.14         2365.89
Permanent Ineff=
       F       F
Bank Sta=535.25,551
XS Rating Curve= 0 ,0
Exp/Cntr=0.3,0.1

Type RM Length L Ch R = 1 ,36913.4 ,30.7,30.7,30.7
XS GIS Cut Line= 2
     2110445.306      184151.128     2110756.563      185259.141
#Sta/Elev= 30
       0 2449.92    49.2 2449.64   131.2 2443.04   291.8 2403.18   390.2 2371.69
   432.8  2363.3   449.2  2361.3  473.242360.573  517.262360.768  519.992360.781
   554.1 2362.09  559.962361.188   567.2 2360.35   573.8 2361.19  577.332361.639
     646 2366.93  667.832370.075   691.8 2369.24   704.52372.886   744.3 2375.93
   760.7 2378.81   806.6 2381.35   885.3 2399.25     905 2401.57   931.2 2402.38
  1029.6 2418.16  1065.6 2428.88  1088.6 2432.66    1128 2436.73  1150.9 2444.83
#Mann= 9 ,-1 , 0
       0     .12       0  473.24     .06       0  517.26     .12       0
  519.99     .06       0  559.96    .045       0   573.8     .06       0
  577.33     .12       0  667.83    .016       0   704.5     .12       0
Bank Sta=559.96,573.8
XS Rating Curve= 0 ,0
Exp/Cntr=0.3,0.1

Type RM Length L Ch R = 1 ,36882.7 ,219.8,212,204.1
XS GIS Cut Line= 2
     2110417.528      184165.885     2110728.785      185273.898
#Sta/Elev= 30
       0  2452.3    62.3 2452.22   124.6 2446.17   291.8 2404.56   429.5 2365.23
   449.2 2361.57  463.672360.779     4852360.366  512.672360.541   554.1 2360.98
   560.7 2359.83  568.992360.985   613.2 2363.24  661.762368.509   691.8 2368.65
  708.052372.749   731.2 2375.83   744.3 2375.33   783.7    2381     823 2393.41
   875.5 2407.65   911.5 2414.72   980.4 2422.89  1013.2 2429.98    1023 2430.38
    1046 2426.25  1075.5 2427.15  1124.7 2436.46  1144.3 2436.27  1150.9  2438.1
#Mann= 8 ,-1 , 0
       0     .12       0  463.67     .06       0     485     .12       0
  512.67     .06       0   554.1    .045       0  568.99     .12       0
  661.76    .016       0  708.05     .12       0
Bank Sta=554.1,568.99
XS Rating Curve= 0 ,0
Exp/Cntr=0.3,0.1

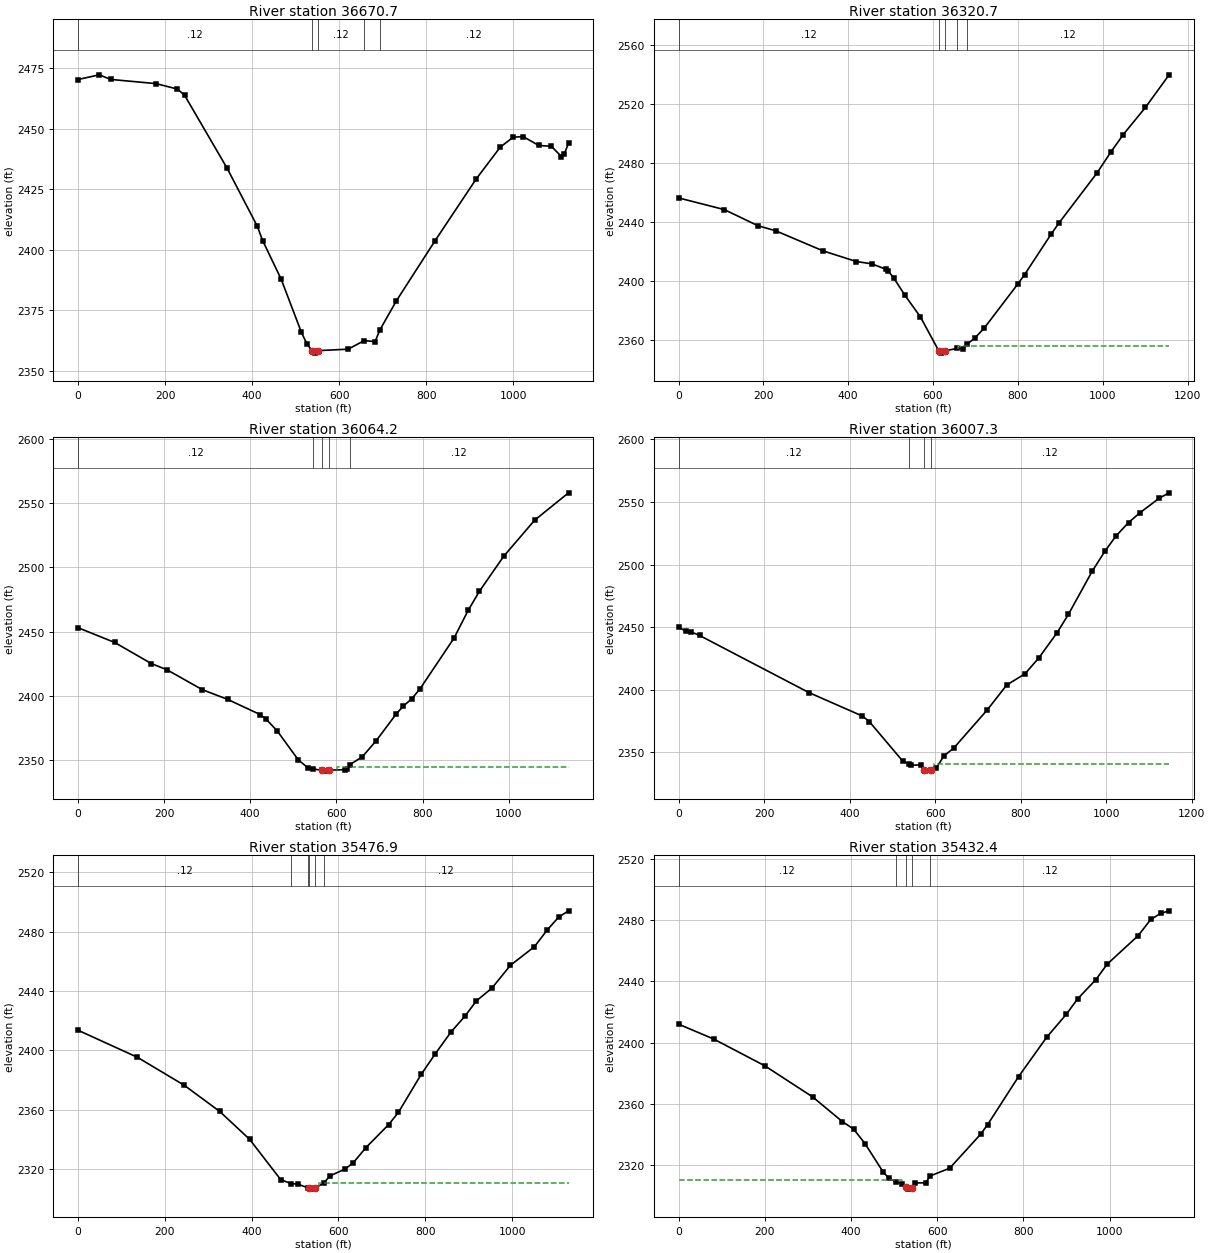
Type RM Length L Ch R = 1 ,36670.7 ,342.4,350,361.8
XS GIS Cut Line= 3
     2110069.723      184375.775      2110391.72      184815.892
     2110731.293      185287.932
#Sta/Elev= 30
       0  2470.4      49 2472.34    75.1 2470.44   179.6  2468.7   228.6 2466.45
   244.9 2463.91   342.9 2433.66   411.4 2409.98   424.5 2403.76     467 2387.82
   512.7  2366.2   525.7 2361.21   537.8 2358.41   545.3 2357.36  550.732358.386
   620.5 2358.99  657.432362.526   682.5 2362.12  693.512366.935   731.5 2378.99
   819.7 2403.65   914.5 2429.26     970 2442.47   999.4 2446.54  1022.3 2446.85
  1058.2 2443.18  1087.6 2442.79  1110.5 2438.58    1117  2439.7  1126.8 2444.07
#Mann= 5 ,-1 , 0
       0     .12       0   537.8    .045       0  550.73     .12       0
  657.43    .016       0  693.51     .12       0
Bank Sta=537.8,550.73
XS Rating Curve= 0 ,0
Exp/Cntr=0.3,0.1

Type RM Length L Ch R = 1 ,36320.7 ,270.4,256.5,233.6
XS GIS Cut Line= 3
     2109986.584      184421.473     2110135.847      185025.651
     2110169.876      185558.654
#Sta/Elev= 30
       0 2456.15   108.1  2448.2   186.7 2437.33   229.3 2433.82   340.6 2420.22
   419.3 2412.99   455.3 2411.44     488 2407.86   494.6 2406.49   507.7 2401.68
   533.9 2390.02   569.9 2375.57  613.432352.459   615.8 2351.33   619.1 2350.88
   628.9 2352.45  655.892354.039   671.5 2353.75  679.712356.954   697.7 2360.85
   720.6 2367.85   799.3 2397.56   815.7  2404.1   877.9  2431.4   897.6 2439.43
     986 2472.86  1018.8  2487.1  1048.3  2499.1  1100.7 2517.52  1156.4  2539.6
#Mann= 5 ,-1 , 0
       0     .12       0  613.43    .045       0   628.9     .12       0
  655.89    .016       0  679.71     .12       0
#XS Ineff= 2 , 0
                          659.87         2355.44
Permanent Ineff=
       F       F
Bank Sta=613.43,628.9
XS Rating Curve= 0 ,0
Exp/Cntr=0.3,0.1

Type RM Length L Ch R = 1 ,36064.2 ,35.8,56.9,52.6
XS GIS Cut Line= 4
     2109966.411      184419.189     2109876.568      184959.554
     2109922.141      184986.898     2109867.453      185522.054
#Sta/Elev= 30
       0 2453.02    85.3  2441.5   170.6 2425.02   206.6 2420.25   288.6 2404.78
   347.7 2397.14   423.1 2385.33   436.3 2381.96   462.5 2372.67   511.7 2350.01
   534.7  2343.7  546.482342.916   566.5 2341.98   575.9  2341.3   582.2 2342.05
   620.6 2342.42   623.9 2342.83  630.972346.303     660 2352.42   692.8 2365.14
   738.7 2385.73   755.1 2391.89   774.8 2397.57   794.5 2405.57   873.2 2444.98
     906 2466.57   932.2 2481.46     988 2508.47  1060.2 2536.72  1138.9 2558.05
#Mann= 5 ,-1 , 0
       0     .12       0  546.48    .016       0   566.5    .045       0
   582.2    .016       0  630.97     .12       0
#XS Ineff= 2 , 0
                          602.11         2344.62
Permanent Ineff=
       F       F
Bank Sta=566.5,582.2
XS Rating Curve= 0 ,0
Exp/Cntr=0.3,0.1

Type RM Length L Ch R = 1 ,36007.3 ,505.4,530.4,579.9
XS GIS Cut Line= 4
     2109935.161      184413.981     2109838.807      184982.991
      2109884.38      185010.335     2109833.599      185524.658
#Sta/Elev= 30
       0 2449.95    16.4 2446.83    29.5 2446.19    49.2 2443.32     305 2397.69
   429.6 2378.99     446 2374.57   524.6 2342.83  538.872340.883   544.3 2339.64
   567.3 2339.98  574.952336.053   577.1 2334.95   589.6 2336.19   602.1 2337.11
   620.9 2347.27   643.3 2353.26   721.8 2383.81   767.6 2403.82   810.2 2412.71
   842.9 2425.57   885.4 2445.64   911.6 2460.14   967.2 2494.58   996.6  2510.4
  1022.8 2522.76  1052.2 2533.47  1078.4 2541.19  1124.2    2553  1147.1 2557.26
#Mann= 4 ,-1 , 0
       0     .12       0  538.87    .016       0  574.95    .045       0
   589.6     .12       0
#XS Ineff= 2 , 0
                          596.69         2340.78
Permanent Ineff=
       F       F
Bank Sta=574.95,589.6
XS Rating Curve= 0 ,0
Exp/Cntr=0.3,0.1

Type RM Length L Ch R = 1 ,35476.9 ,33.6,44.5,33.8
XS GIS Cut Line= 4
     2109519.276      184320.513     2109387.983      184826.155
      2109348.92      184832.666     2109309.858      185399.072
#Sta/Elev= 30
       0 2413.65   137.1 2395.41   244.9 2376.59   326.5    2359   395.1 2340.34
   466.9 2313.16  491.272310.414   506.1 2310.19  530.542307.465   531.6 2307.39
   540.7 2306.75   546.8 2307.39  565.87 2310.93   581.6 2315.86   614.2 2320.07
   633.8 2324.38   663.2 2334.69   715.4 2350.11   738.2 2358.46   790.4 2383.89
     823 2397.81   858.9 2412.36   891.6  2423.2   917.7  2433.4   953.6 2442.03
     996 2457.31  1051.4 2469.86  1080.8 2481.09  1106.9 2489.68  1129.8 2493.95
#Mann= 6 ,-1 , 0
       0     .12       0  491.27    .016       0  530.54     .12       0
   531.6    .045       0   546.8    .016       0  565.87     .12       0
#XS Ineff= 2 , 0
                          555.34         2311.03
Permanent Ineff=
       F       F
Bank Sta=531.6,546.8
XS Rating Curve= 0 ,0
Exp/Cntr=0.3,0.1

Type RM Length L Ch R = 1 ,35432.4 ,185.2,150.2,134
XS GIS Cut Line= 4
     2109489.979      184311.832     2109363.026      184796.859
     2109323.963      184803.369     2109282.731      185399.072
#Sta/Elev= 30
       0 2412.07    81.9 2402.29   199.9 2384.88   311.3 2364.46   380.1 2348.36
   406.3 2343.44   432.6 2333.99   475.2 2315.22   488.3 2311.29  505.012308.927
   519.6 2307.67  527.542305.323   531.8 2304.21     541 2305.27   547.5 2308.24
   573.6 2308.35  583.682312.806   629.1 2317.89   700.8 2340.09   717.2 2346.44
     789 2377.82   854.2 2403.52   899.9 2418.61     926 2428.61   968.4 2441.24
   994.5 2451.29  1066.3 2469.92  1095.7 2480.55  1118.5 2484.46  1138.1 2486.15
#Mann= 5 ,-1 , 0
       0     .12       0  505.01    .016       0  527.54    .045       0
     541    .016       0  583.68     .12       0
#XS Ineff= 2 , 0
          518.19 2310.18
Permanent Ineff=
       F       F
Bank Sta=527.54,541
XS Rating Curve= 0 ,0
Exp/Cntr=0.3,0.1

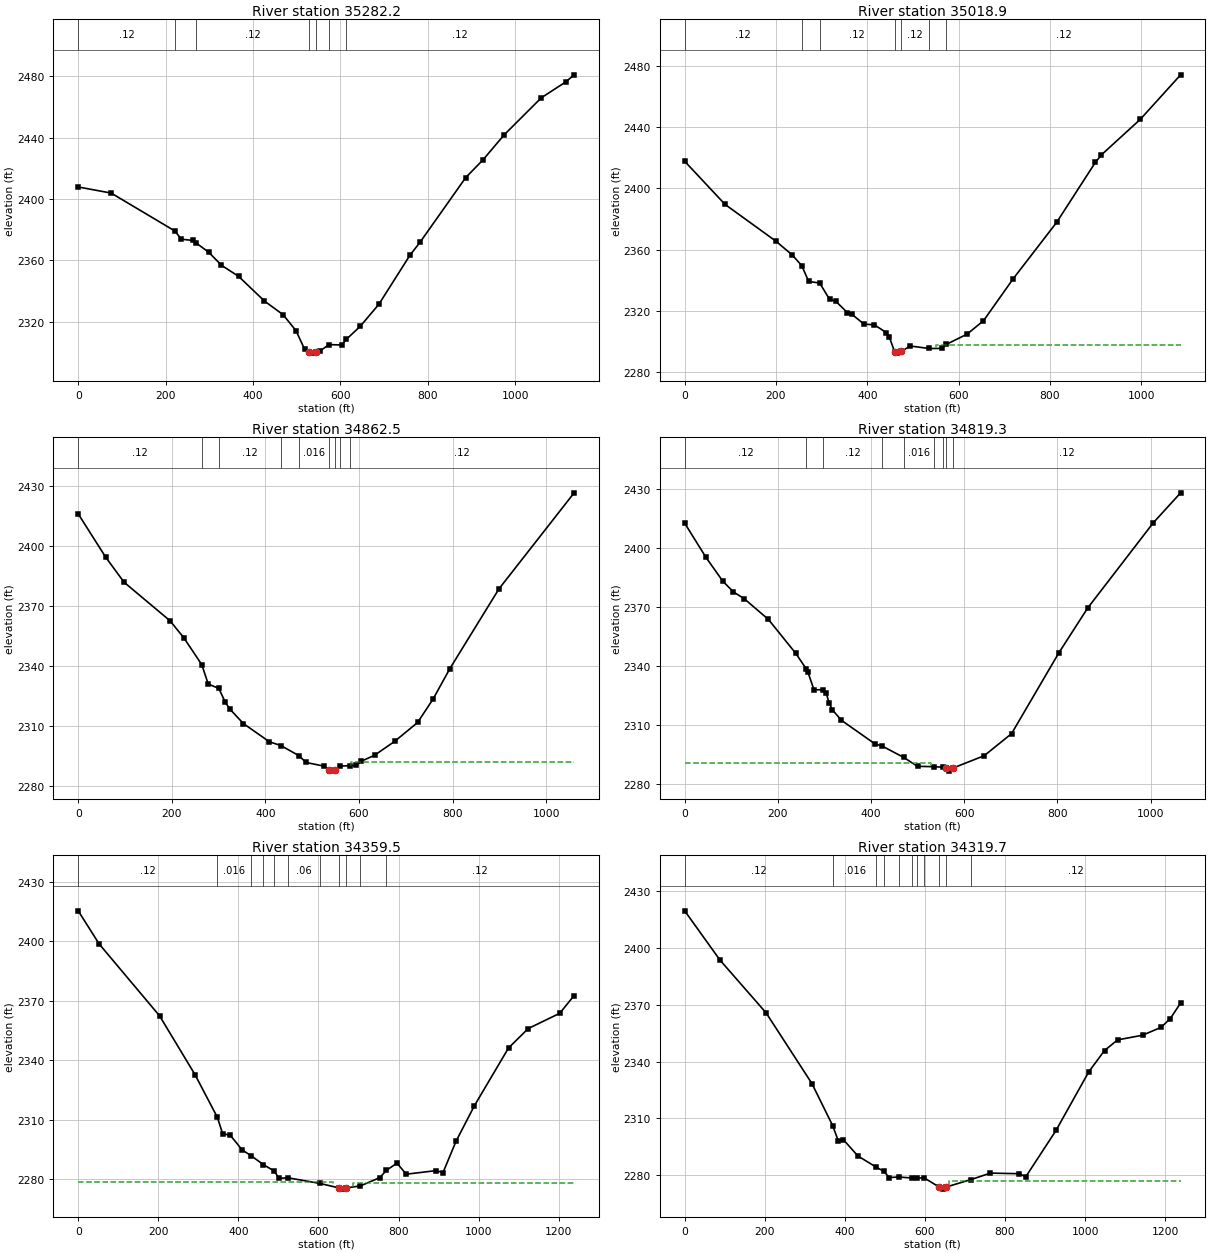
Type RM Length L Ch R = 1 ,35282.2 ,274.3,263.3,253.8
XS GIS Cut Line= 3
     2109169.602      184275.693     2109187.347      184813.078
     2109265.606      185405.225
#Sta/Elev= 30
       0 2407.91    75.4 2403.94  221.252379.205     236 2373.86   262.3 2373.05
  269.552371.431   298.4 2365.45   327.8  2356.9   367.2  2349.6   426.2 2333.55
   468.8 2324.67   498.3 2314.28     518 2302.21   527.8 2300.45   537.7 2299.59
   544.2 2300.62     554 2301.14  574.162305.164     603 2304.88  613.572308.571
   645.4 2317.06   687.8 2331.32   759.6 2363.59   782.5 2371.95   886.9 2414.06
   926.1 2425.51     975 2441.95  1059.9 2466.08  1115.4 2476.33    1135 2481.03
#Mann= 7 ,-1 , 0
       0     .12       0  221.25    .016       0  269.55     .12       0
   527.8    .045       0   544.2     .12       0  574.16    .016       0
  613.57     .12       0
Bank Sta=527.8,544.2
XS Rating Curve= 0 ,0
Exp/Cntr=0.3,0.1

Type RM Length L Ch R = 1 ,35018.9 ,167,156.4,132.7
XS GIS Cut Line= 2
     2108735.443      184448.145     2109241.086      185409.516
#Sta/Elev= 30
       0 2417.59    88.3  2389.5   199.6 2365.54   235.6 2356.51  256.37 2349.55
   271.6 2339.23  295.682338.204   317.4 2327.55   330.4  2326.5   356.6 2318.84
   366.4 2317.81   392.6 2311.41   415.5 2310.95   441.7 2305.87   448.2 2303.03
   459.6 2293.52   464.6  2292.5   474.6 2293.61     494 2297.14  535.332295.525
   562.8 2295.56  572.822298.173   618.4 2304.85   654.4  2313.6   719.8 2341.11
   814.7 2377.76   899.7 2416.96   912.8 2421.79   997.9 2444.95  1086.2 2473.96
#Mann= 7 ,-1 , 0
       0     .12       0  256.37    .016       0  295.68     .12       0
   459.6    .045       0   474.6     .12       0  535.33    .016       0
  572.82     .12       0
#XS Ineff= 2 , 0
                          551.25         2297.96
Permanent Ineff=
       F       F
Bank Sta=459.6,474.6
XS Rating Curve= 0 ,0
Exp/Cntr=0.3,0.1

Type RM Length L Ch R = 1 ,34862.5 ,46.2,43.1,42.5
XS GIS Cut Line= 4
     2108704.895      184455.185     2108822.083      184964.734
     2108863.749       184966.47     2108992.221      185444.768
#Sta/Elev= 30
       0 2416.24    58.8 2394.52      98    2382   196.1 2362.72   225.5 2354.24
  264.072340.712   277.8 2331.04  300.552328.804   313.7 2322.15   323.5  2318.6
   352.9 2311.23   408.5 2302.09   432.82300.222  471.442295.171   486.9 2291.72
   526.1 2289.85  535.392288.043   538.9 2287.39  548.492288.049  559.022289.886
  581.292290.135   594.1 2290.21   603.9 2292.25   633.4 2295.35   676.1 2302.27
   725.3 2311.76   758.1  2323.4   794.1 2338.69   899.1 2378.68  1059.8 2426.79
#Mann= 9 ,-1 , 0
       0     .12       0  264.07    .016       0  300.55     .12       0
   432.8     .06       0  471.44    .016       0  535.39    .045       0
  548.49     .12       0  559.02    .016       0  581.29     .12       0
#XS Ineff= 2 , 0
                          581.98         2292.07
Permanent Ineff=
       F       F
Bank Sta=535.39,548.49
XS Rating Curve= 0 ,0
Exp/Cntr=0.3,0.1

Type RM Length L Ch R = 1 ,34819.3 ,427.1,459.8,501.6
XS GIS Cut Line= 4
     2108684.756      184467.251     2108807.152      185005.445
     2108848.819      185007.182     2108972.951      185461.175
#Sta/Elev= 30
       0 2412.41    45.7 2395.01    81.6 2383.01   104.5 2377.47   127.4 2374.09
   179.6 2363.51   238.4 2346.26  260.682338.462   264.5 2336.67   277.6 2327.72
  296.482327.793   303.7 2325.98   310.3  2320.9   316.8 2317.58   336.4 2312.25
   408.2 2300.28  424.072299.122  469.99 2293.39   499.7 2288.86  535.022288.677
  554.752288.423   561.62288.105     568 2286.42  576.832288.086   642.7 2294.24
   701.5 2305.46   802.8 2346.46   864.9 2369.31  1005.5 2412.55  1064.3 2427.82
#Mann= 9 ,-1 , 0
       0     .12       0  260.68    .016       0  296.48     .12       0
  424.07     .06       0  469.99    .016       0  535.02     .06       0
  554.75     .12       0   561.6    .045       0  576.83     .12       0
#XS Ineff= 2 , 0
          529.06 2290.32
Permanent Ineff=
       F       F
Bank Sta=561.6,576.83
XS Rating Curve= 0 ,0
Exp/Cntr=0.3,0.1

Type RM Length L Ch R = 1 ,34359.5 ,42.9,39.8,39.7
XS GIS Cut Line= 2
     2108608.541      184459.439     2108233.541      185639.994
#Sta/Elev= 30
       0 2415.36    52.4 2398.63   203.2 2362.41   291.6 2332.81  347.652311.236
   360.5 2303.09   380.1 2302.13   409.6 2294.82  431.582291.919  462.582287.404
  489.432284.182   501.4 2280.51  524.562280.746  603.112277.946   652.1 2275.63
   658.7 2275.05   668.5 2275.64  704.632276.653   753.7 2280.89  769.582284.531
   796.3 2288.13   819.2 2282.58   894.6  2284.4     911 2283.32   943.8 2299.24
   989.6 2317.12  1074.8 2346.23    1124    2356  1202.6 2363.69  1238.7 2372.66
#Mann= 11 ,-1 , 0
       0     .12       0  347.65    .016       0  431.58     .12       0
  462.58     .06       0  489.43    .016       0  524.56     .06       0
  603.11     .12       0   652.1    .045       0   668.5     .12       0
  704.63    .016       0  769.58     .12       0
#XS Ineff= 2 , 0
          635.94 2278.74  686.88         2278.38
Permanent Ineff=
       F       F
Bank Sta=652.1,668.5
XS Rating Curve= 0 ,0
Exp/Cntr=0.3,0.1

Type RM Length L Ch R = 1 ,34319.7 ,445.6,438.5,425.7
XS GIS Cut Line= 2
     2108571.735      184448.327     2108196.735      185628.883
#Sta/Elev= 30
       0 2419.71    88.5 2393.57   203.2 2365.79   317.9 2328.32  369.662306.086
   383.4 2298.21   396.5 2298.66   432.6 2290.05  478.992284.061  496.992281.978
   511.2 2278.66  536.212278.909  567.212278.388  579.092278.347   598.2 2278.47
   635.7  2273.6   645.6 2272.51   652.1 2273.56  715.332277.575   763.5 2280.98
   835.6 2280.67     852 2279.06   927.4 2303.52  1009.3 2334.55  1048.6 2345.82
  1081.4 2351.45  1143.6 2353.92  1189.5 2358.05  1212.5 2362.58  1238.7 2370.96
#Mann= 11 ,-1 , 0
       0     .12       0  369.66    .016       0  478.99     .06       0
  496.99    .016       0  536.21     .06       0  567.21     .12       0
  579.09     .06       0   598.2     .12       0   635.7    .045       0
   652.1    .016       0  715.33     .12       0
#XS Ineff= 2 , 0
                          659.21         2276.79
Permanent Ineff=
       F       F
Bank Sta=635.7,652.1
XS Rating Curve= 0 ,0
Exp/Cntr=0.3,0.1

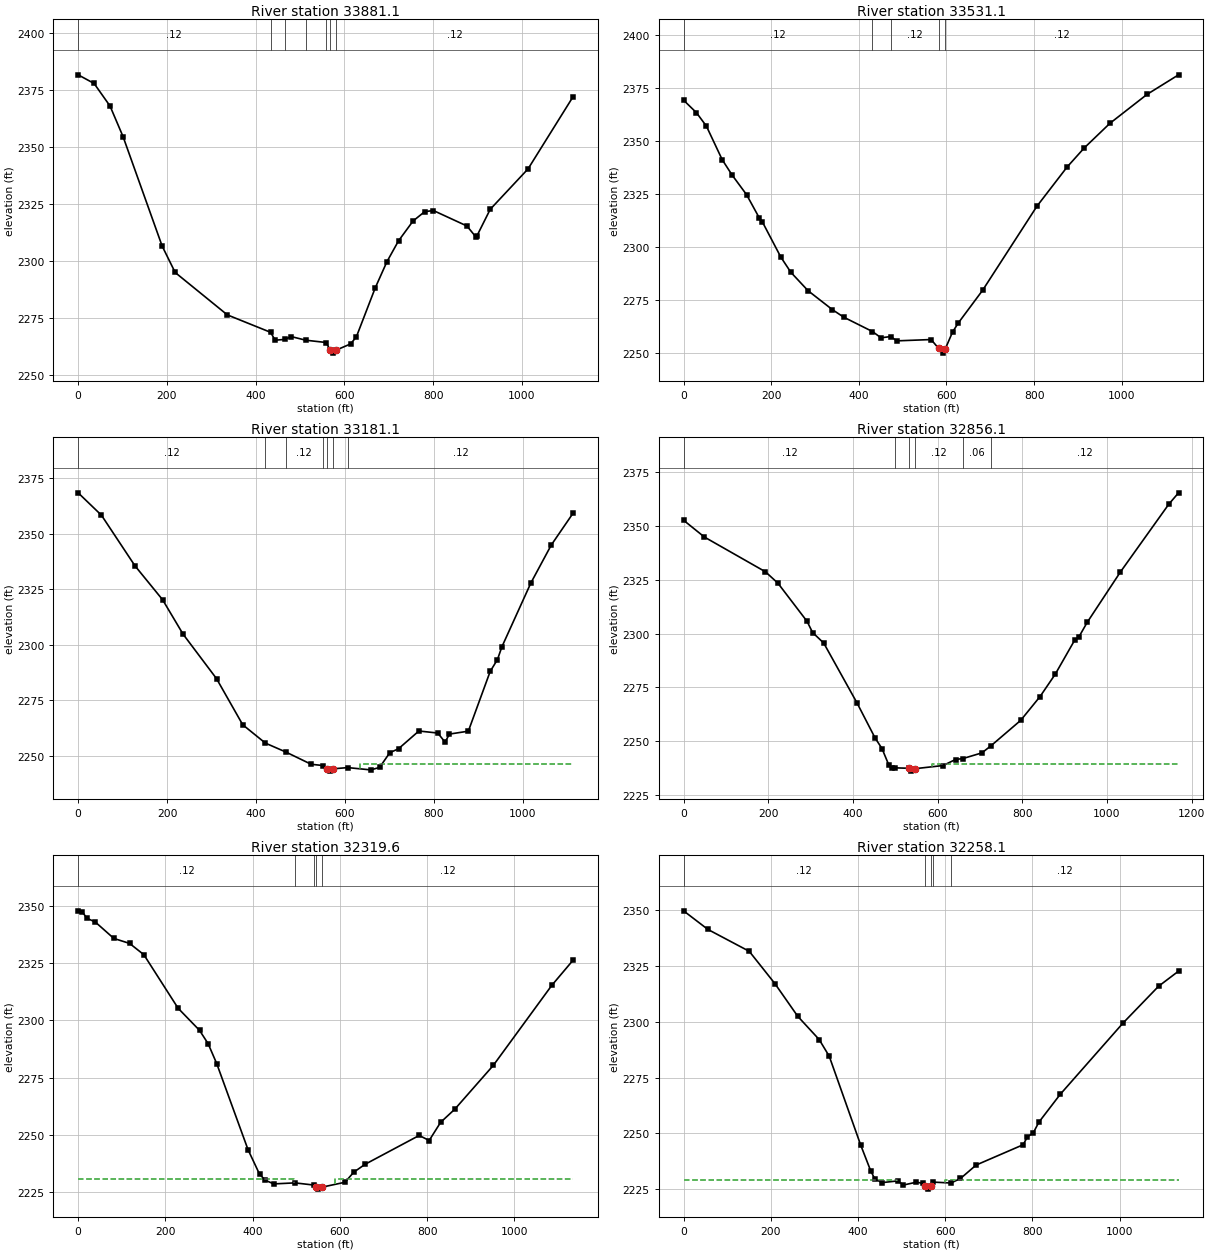
Type RM Length L Ch R = 1 ,33881.1 ,340.1,350,360
XS GIS Cut Line= 3
     2107881.446      184530.972     2107978.237      185097.025
     2108104.413       185623.07
#Sta/Elev= 30
       0 2381.77    35.9 2377.98    71.8 2368.08   101.2 2354.62   189.2 2306.64
   218.6 2295.03   336.1 2276.43  433.482268.791   443.8 2265.33  466.372265.679
   479.6 2266.93  512.862265.319   559.22264.301   566.8 2261.16   574.3 2259.65
   581.8 2261.02   613.6 2263.67   626.7 2266.74   669.4 2288.32   695.6 2299.74
   721.8 2308.93   754.6 2317.64   780.8 2321.74   800.5 2322.21   875.9 2315.44
   895.6 2310.76   898.8 2311.23   928.4 2322.76  1013.6 2340.49  1115.2 2372.22
#Mann= 7 ,-1 , 0
       0     .12       0  433.48    .016       0  466.37     .12       0
  512.86     .06       0   559.2     .12       0   566.8    .045       0
   581.8     .12       0
Bank Sta=566.8,581.8
XS Rating Curve= 0 ,0
Exp/Cntr=0.3,0.1

Type RM Length L Ch R = 1 ,33531.1 ,340.3,350,364.1
XS GIS Cut Line= 3
     2107781.135      184529.894     2107634.555      185102.417
     2107519.888      185628.619
#Sta/Elev= 30
       0 2369.09    29.4  2363.2    52.2 2356.82    88.2    2341     111  2333.7
   143.7 2324.53     173 2313.46   179.6 2311.75     222 2295.03   244.9 2287.86
   284.1 2279.19   339.6 2270.25   365.7 2266.67  431.042259.917   450.6 2256.96
  472.57 2257.55   486.5 2255.52   564.9 2256.14  582.162251.929     591 2249.73
   597.5 2251.86   613.8 2259.68   626.9 2263.95   682.4 2279.38   806.4 2319.06
     875  2337.5   914.1 2346.51   972.9 2358.17  1057.7 2371.84  1129.5 2381.06
#Mann= 5 ,-1 , 0
       0     .12       0  431.04    .016       0  472.57     .12       0
  582.16    .045       0   597.5     .12       0
Bank Sta=582.16,597.5
XS Rating Curve= 0 ,0
Exp/Cntr=0.3,0.1

Type RM Length L Ch R = 1 ,33181.1 ,336,325,306.8
XS GIS Cut Line= 3
     2107693.303      184482.482     2107340.016       184929.44
     2106932.019      185287.829
#Sta/Elev= 30
       0 2368.46    52.4 2358.37   127.7 2335.61   189.9 2320.32   235.8 2304.87
   311.1 2284.82     370 2264.07   420.92255.823  467.082251.792   523.9 2246.29
  549.982245.738   559.9 2244.13   566.4 2243.21     573 2244.24  606.022244.801
     658 2243.76   677.7 2244.89   700.6 2251.49   720.2 2253.28     766 2261.27
   808.5 2260.35   824.9 2256.24   834.7 2259.88   877.2 2261.19   926.3 2288.08
   942.7 2293.44   952.5 2299.09  1017.9 2327.94  1063.7 2344.99  1112.8 2359.34
#Mann= 7 ,-1 , 0
       0     .12       0   420.9    .016       0  467.08     .12       0
  549.98     .06       0   559.9    .045       0     573     .06       0
  606.02     .12       0
#XS Ineff= 2 , 0
                          632.57         2246.63
Permanent Ineff=
       F       F
Bank Sta=559.9,573
XS Rating Curve= 0 ,0
Exp/Cntr=0.3,0.1

Type RM Length L Ch R = 1 ,32856.1 ,506.1,536.5,566.3
XS GIS Cut Line= 3
     2107205.495      184144.325       2107125.2       184840.94
     2106871.294      185233.735
#Sta/Elev= 30
       0 2352.72    49.2 2344.91   193.3 2328.75   222.8 2323.45   291.6 2305.69
   304.7 2300.49     331 2295.58   409.6 2267.73   452.2 2251.45   468.6 2246.49
     485  2238.7   491.5 2237.35  500.02 2237.52   531.2 2237.32   537.4 2235.99
   546.2 2237.12   612.8 2238.59   642.2  2241.4  659.942241.854   704.5 2244.48
  726.142247.806   796.1  2259.6   841.9  2270.7   877.8  2281.1   923.6 2296.92
   933.4 2298.36   953.1 2305.18  1031.6 2328.64    1146 2360.21  1168.9 2365.48
#Mann= 6 ,-1 , 0
       0     .12       0  500.02    .016       0   531.2    .045       0
   546.2     .12       0  659.94     .06       0  726.14     .12       0
#XS Ineff= 2 , 0
                          586.35         2239.32
Permanent Ineff=
       F       F
Bank Sta=531.2,546.2
XS Rating Curve= 0 ,0
Exp/Cntr=0.3,0.1

Type RM Length L Ch R = 1 ,32319.6 ,52.9,61.5,53.5
XS GIS Cut Line= 4
     2106986.087      184031.531     2106720.245      184490.515
     2106674.672      184488.345     2106358.917      184949.499
#Sta/Elev= 30
       0 2347.79     9.8 2347.34    19.6 2344.58    39.3  2342.9    81.8 2335.74
   117.9 2333.57   150.6 2328.65   229.2 2305.27   278.3 2295.63     298  2289.8
   317.6 2281.16   389.6  2243.5   415.8  2232.9   428.9 2230.22   448.6 2228.62
  497.122229.065   540.82228.106  545.56 2227.18     550 2226.34   559.8 2227.23
     612 2229.35   631.6 2233.69   657.8 2237.17     782 2249.77   804.8 2247.56
     831 2255.47   863.7 2261.25   951.9 2280.35  1085.9 2315.25  1134.9 2326.28
#Mann= 5 ,-1 , 0
       0     .12       0  497.12    .016       0   540.8     .12       0
  545.56    .045       0   559.8     .12       0
#XS Ineff= 2 , 0
          494.19 2230.64  587.78         2230.64
Permanent Ineff=
       F       F
Bank Sta=545.56,559.8
XS Rating Curve= 0 ,0
Exp/Cntr=0.3,0.1

Type RM Length L Ch R = 1 ,32258.1 ,174.2,148.2,135.1
XS GIS Cut Line= 4
     2106953.058       183987.13     2106687.216      184446.114
     2106641.643      184443.944     2106325.887      184905.098
#Sta/Elev= 30
       0  2349.7    55.7 2341.38   150.6 2331.57   209.6 2317.06   261.9 2302.44
     311 2292.04     334 2284.58     406 2244.87   428.9 2233.34   438.7 2229.54
   455.1 2227.98   491.1 2228.74   504.2  2226.9   533.7 2228.16     550 2227.62
   553.2 2226.58   559.7 2225.06  567.33 2226.64  572.992228.201  613.062227.802
   634.9 2229.82   670.8 2235.84   778.7 2244.95   788.5 2248.53   801.6 2250.17
   814.6 2255.02   863.7 2267.53  1007.5 2299.41  1089.2 2315.93  1134.9 2322.68
#Mann= 5 ,-1 , 0
       0     .12       0   553.2    .045       0  567.33     .12       0
  572.99    .016       0  613.06     .12       0
#XS Ineff= 2 , 0
          489.74 2229.37   598.7         2229.28
Permanent Ineff=
       F       F
Bank Sta=553.2,567.33
XS Rating Curve= 0 ,0
Exp/Cntr=0.3,0.1

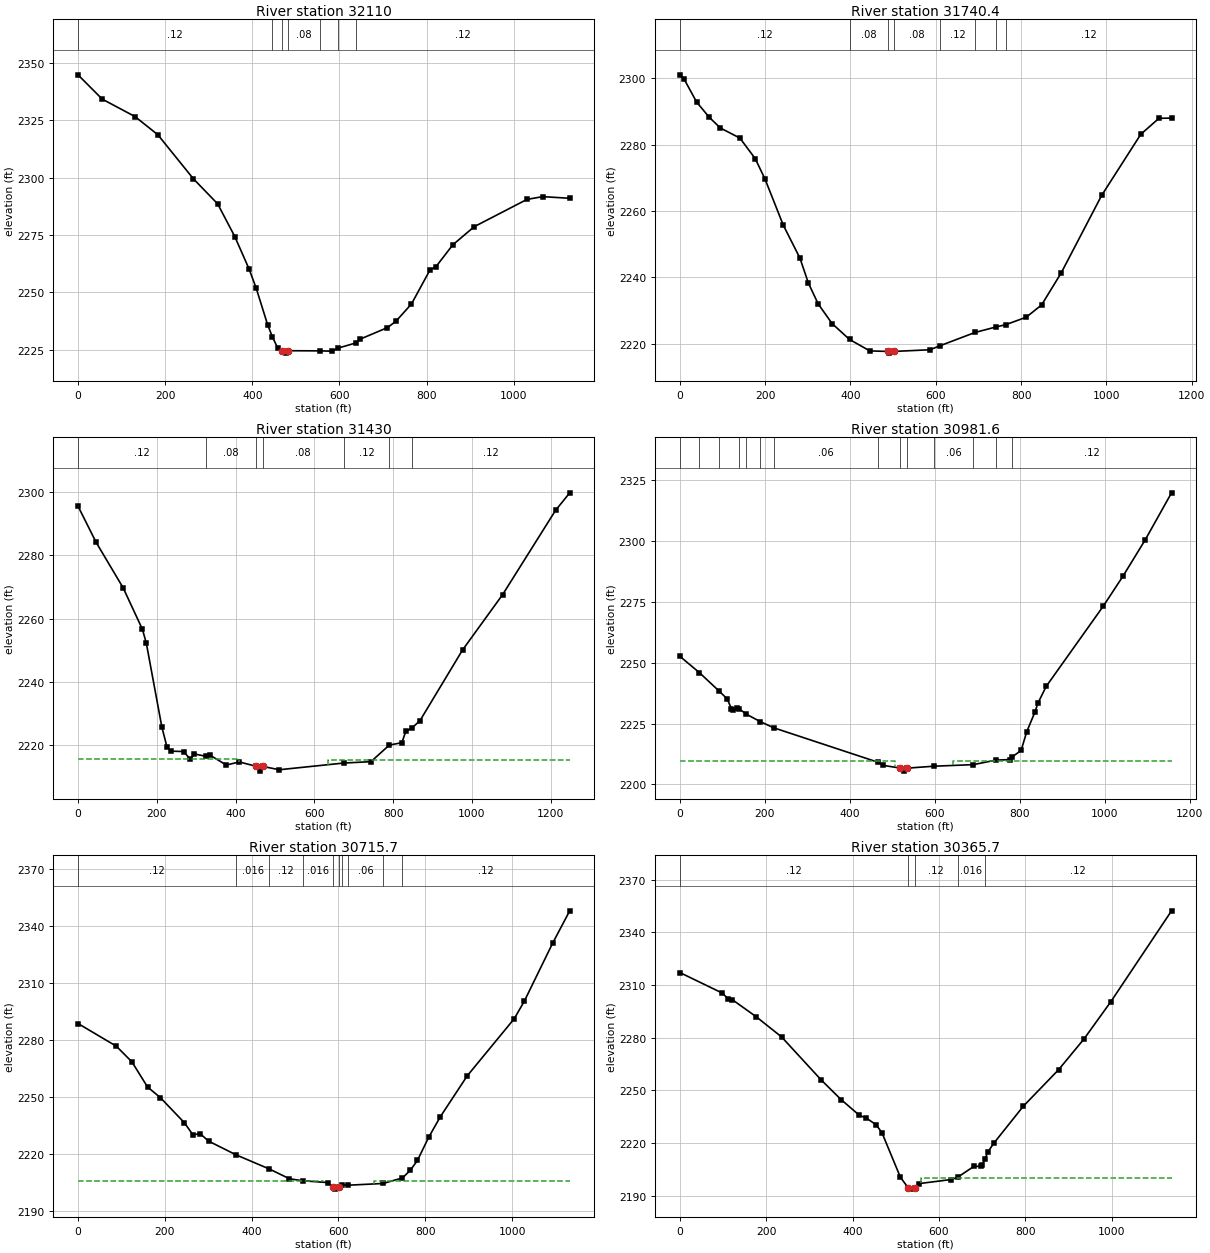
Type RM Length L Ch R = 1 ,32110   ,362.8,369.6,369.7
XS GIS Cut Line= 2
     2106862.613      183933.822     2106202.891       184849.62
#Sta/Elev= 30
       0 2344.85    55.6 2334.25   130.9 2326.64   183.2 2318.72     265 2299.47
   320.6 2288.56   359.9  2274.3   392.6 2260.19   408.9 2251.87   435.1 2235.93
  446.272230.504     458 2225.88   467.8 2224.52   477.6 2223.46  482.992224.514
  555.442224.449   582.3 2224.31  597.922225.703  638.192227.926   647.8 2229.57
   709.9 2234.56   729.6 2237.31   765.5 2244.92   808.1 2259.78   821.2 2261.05
   860.4 2270.71   909.5 2278.61  1030.5  2290.5  1066.5 2291.72  1128.7    2291
#Mann= 7 ,-1 , 0
       0     .12       0  446.27     .08       0   467.8    .045       0
  482.99     .08       0  555.44     .12       0  597.92    .016       0
  638.19     .12       0
Bank Sta=467.8,482.99
XS Rating Curve= 0 ,0
Exp/Cntr=0.3,0.1

Type RM Length L Ch R = 1 ,31740.4 ,314.4,310.4,303.7
XS GIS Cut Line= 2
     2106563.134      183734.169     2105914.263       184686.86
#Sta/Elev= 30
       0 2301.01     9.8 2299.78    39.3 2292.82    68.8 2288.24      95    2285
   140.8 2281.96   176.8 2275.76   199.8 2269.58   242.3 2255.79   281.6 2245.79
   301.3 2238.31   324.2 2232.04   356.9 2226.09  397.752221.304   445.4 2217.85
  486.952217.691   491.2 2217.18     501 2217.69   586.2 2218.19  609.522219.379
  691.892223.401  740.48 2225.04  764.082225.753   812.1    2228   848.1  2231.7
     894 2241.34   988.9  2264.7  1080.6  2283.1  1123.2 2287.91  1152.7 2287.98
#Mann= 8 ,-1 , 0
       0     .12       0  397.75     .08       0  486.95    .045       0
     501     .08       0  609.52     .12       0  691.89    .016       0
  740.48     .06       0  764.08     .12       0
Bank Sta=486.95,501
XS Rating Curve= 0 ,0
Exp/Cntr=0.3,0.1

Type RM Length L Ch R = 1 ,31430   ,436,448.4,398.4
XS GIS Cut Line= 3
     2106530.582      183708.127     2106239.784       183755.87
     2105860.009      184630.436
#Sta/Elev= 30
       0 2295.63    45.8  2284.2   114.6 2269.74   163.7 2256.55   173.5 2252.14
   212.8 2225.67   225.9 2219.25   235.8 2217.98   268.5 2217.86   284.9 2215.36
   294.7  2217.1  324.422216.364     334 2216.79   376.6 2213.58   409.4 2214.56
  452.442213.179   461.8 2211.65   468.4 2213.16   510.9 2212.09   674.72214.213
   743.6 2214.65  790.272219.905   822.2 2220.67     832 2224.26  847.242225.276
   868.1 2227.65   976.2 2250.06  1077.8 2267.58  1212.1 2294.27  1248.2 2299.85
#Mann= 7 ,-1 , 0
       0     .12       0  324.42     .08       0  452.44    .045       0
   468.4     .08       0   674.7     .12       0  790.27    .016       0
  847.24     .12       0
#XS Ineff= 2 , 0
             409 2215.61  634.39         2215.11
Permanent Ineff=
       F       F
Bank Sta=452.44,468.4
XS Rating Curve= 0 ,0
Exp/Cntr=0.3,0.1

Type RM Length L Ch R = 1 ,30981.6 ,235.6,265.9,257.3
XS GIS Cut Line= 2
     2106107.405      183397.798     2105640.825      184456.825
#Sta/Elev= 30
       0 2252.66   45.982245.947   92.312238.376   111.5 2235.13   121.3 2231.13
   124.6 2230.68   134.4 2231.53  140.292230.968  156.86 2228.81  189.142225.812
  221.412223.223  465.332209.141   478.6 2207.79     518 2206.71   527.8 2205.43
   534.4 2206.65   597.32207.446  690.78  2208.1  743.562209.953     777 2210.17
   782.62211.344   803.2 2213.93   816.3 2221.58     836 2229.85   842.5 2233.31
   862.2 2240.27   996.6  2273.3  1042.5  2285.5    1095 2300.47  1157.2 2319.88
#Mann= 14 ,-1 , 0
       0     .12       0   45.98     .06       0   92.31    .016       0
  140.29     .12       0  156.86     .06       0  189.14    .016       0
  221.41     .06       0  465.33     .12       0     518    .045       0
   534.4     .12       0   597.3     .06       0  690.78     .12       0
  743.56    .016       0   782.6     .12       0
#XS Ineff= 2 , 0
          506.52 2209.48  643.32         2209.39
Permanent Ineff=
       F       F
Bank Sta=518,534.4
XS Rating Curve= 0 ,0
Exp/Cntr=0.3,0.1

Type RM Length L Ch R = 1 ,30715.7 ,344.4,350,345.6
XS GIS Cut Line= 3
     2105939.306      183321.311     2105716.343      183872.923
     2105418.624      184320.835
#Sta/Elev= 30
       0 2288.57    88.3 2276.62   124.2  2268.4   160.2 2255.16   189.6  2249.6
   245.2 2236.34   264.8 2229.96   281.1 2230.66   300.8  2226.7  364.162219.461
  441.082211.995   487.1 2206.89  517.372205.831   575.4 2204.88  586.922202.482
   591.7 2201.43   601.5 2202.48  607.322203.684  622.412203.495  702.762204.399
  747.47 2207.33   765.5 2211.31   781.9 2216.51   808.1 2228.78   834.4  2239.4
   896.7 2261.04  1004.9 2291.07  1027.9 2300.17  1093.4 2330.81  1132.8 2347.85
#Mann= 10 ,-1 , 0
       0     .12       0  364.16    .016       0  441.08     .12       0
  517.37    .016       0  586.92    .045       0   601.5    .016       0
  607.32     .12       0  622.41     .06       0  702.76    .016       0
  747.47     .12       0
#XS Ineff= 2 , 0
          565.48 2205.95  682.76         2205.75
Permanent Ineff=
       F       F
Bank Sta=586.92,601.5
XS Rating Curve= 0 ,0
Exp/Cntr=0.3,0.1

Type RM Length L Ch R = 1 ,30365.7 ,276,272.4,271.2
XS GIS Cut Line= 3
     2105735.924      183194.184     2105469.921      183660.816
     2105234.854      184214.898
#Sta/Elev= 30
       0 2317.09    98.2  2305.4   111.4 2302.27   121.2  2301.7   176.9  2291.9
   235.8 2280.38   327.5 2255.87   373.4 2244.72   415.9 2235.74   432.3 2234.11
   455.2 2230.26   468.4  2225.7   510.9 2200.44  528.792194.495   537.1 2193.67
   544.6 2194.53   553.5  2196.8   628.7 2199.14  643.742200.477     681  2206.6
   697.4 2206.68   700.7 2207.24  707.062211.037   713.8 2214.94   726.8 2219.68
   795.5 2240.87   877.3  2261.7   936.2 2279.24   998.4 2300.48    1139 2352.25
#Mann= 5 ,-1 , 0
       0     .12       0  528.79    .045       0   544.6     .12       0
  643.74    .016       0  707.06     .12       0
#XS Ineff= 2 , 0
                          558.32         2199.94
Permanent Ineff=
       F       F
Bank Sta=528.79,544.6
XS Rating Curve= 0 ,0
Exp/Cntr=0.3,0.1