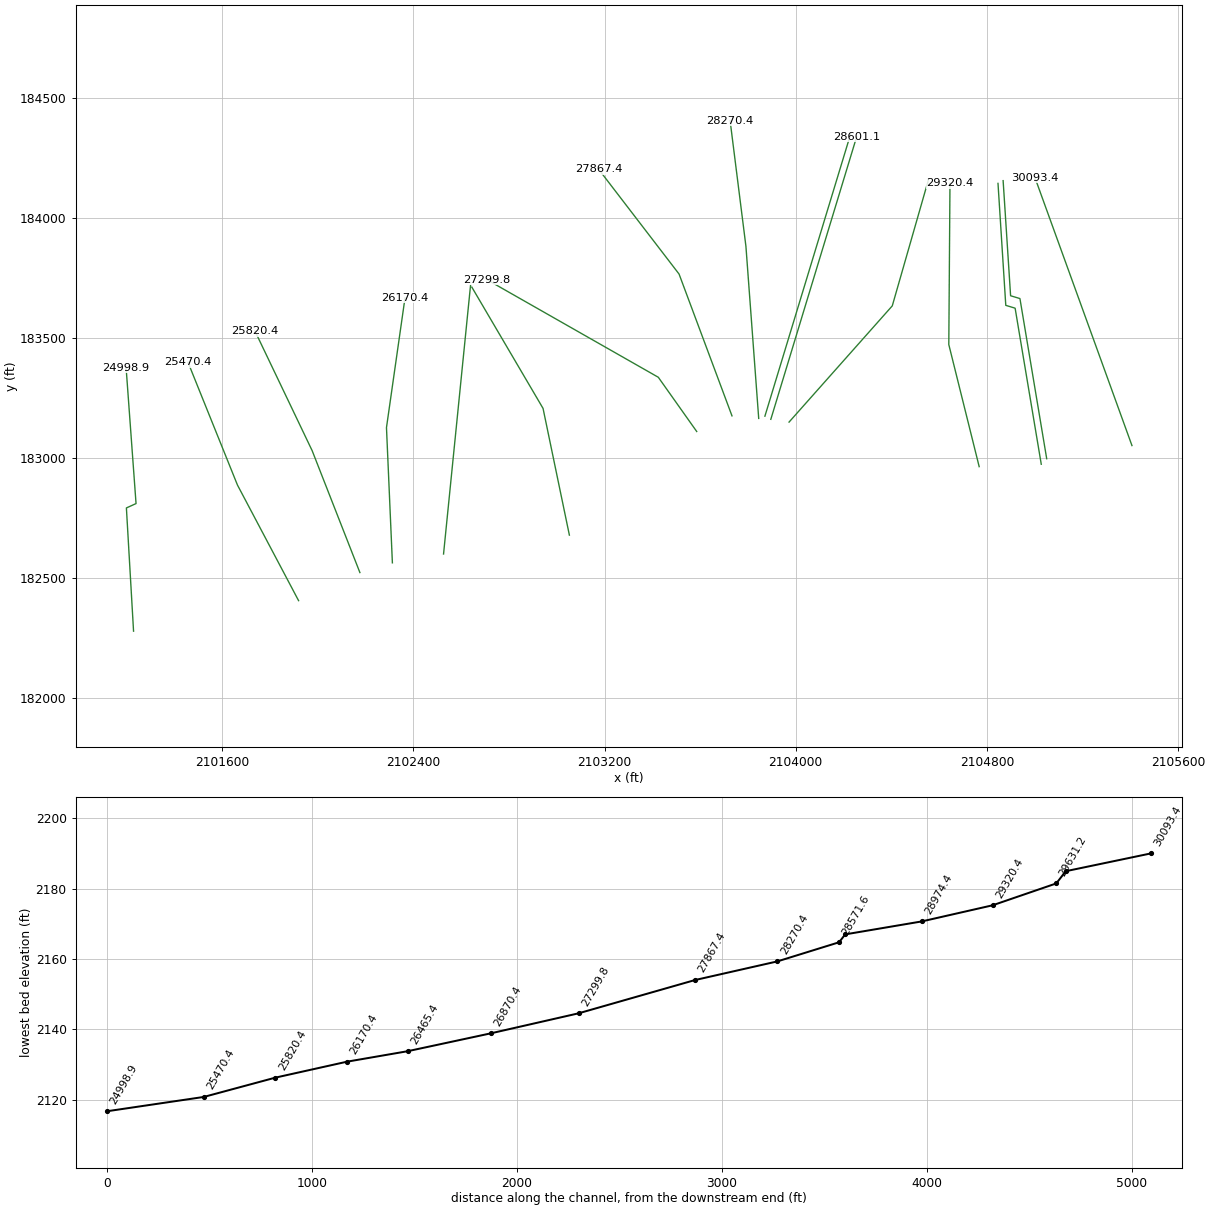
HEC-RAS study DRPLKCR.prj: DRPLKCR

--- DRPLKCR.g01 (geometry) --- (continued)

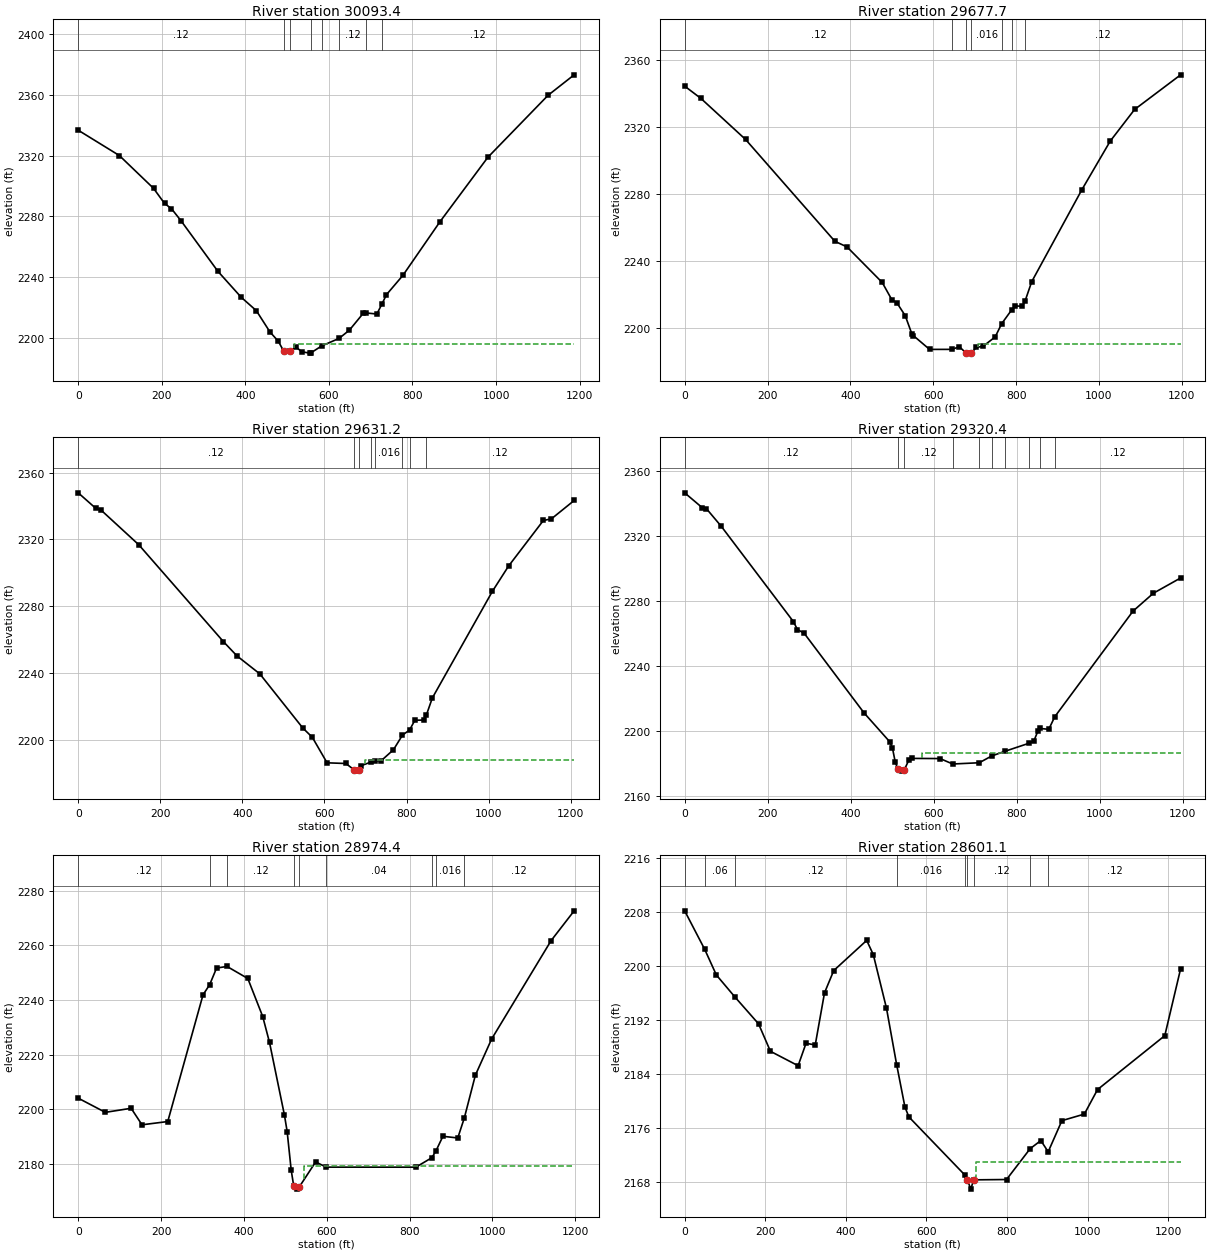
Type RM Length L Ch R = 1 ,30093.4 ,408.6,415.6,435.6
XS GIS Cut Line= 2
      2105406.45      183052.745     2105000.634      184168.197
#Sta/Elev= 30
       0 2336.82    98.4 2320.16   180.3 2298.54   206.6  2288.6     223  2285.2
   245.9 2277.26   334.4 2243.88   390.2 2226.79   426.3    2218     459 2203.94
   478.7 2197.93   491.8 2191.37  505.912191.324   521.4 2194.13   534.5 2190.96
   554.1 2190.03   556.12190.048  582.722194.788   624.2  2199.7   649.2  2205.2
     682 2216.19  689.642216.461   714.8 2215.79  726.962222.377   737.8 2228.54
   777.1 2241.22   865.6 2276.46   980.4 2318.96  1124.7 2359.84    1187 2373.29
#Mann= 8 ,-1 , 0
       0     .12       0   491.8    .045       0  505.91     .12       0
   556.1     .04       0  582.72    .016       0   624.2     .12       0
  689.64    .016       0  726.96     .12       0
#XS Ineff= 2 , 0
                          515.84         2196.09
Permanent Ineff=
       F       F
Bank Sta=491.8,505.91
XS Rating Curve= 0 ,0
Exp/Cntr=0.3,0.1

Type RM Length L Ch R = 1 ,29677.7 ,35.8,46.5,44
XS GIS Cut Line= 4
     2105049.813      182998.034     2104937.834      183664.701
     2104898.772       183676.42     2104867.522      184155.587
#Sta/Elev= 30
       0 2344.13    39.2 2336.81     147 2312.34   362.5 2251.63   391.9 2248.28
   476.8 2227.08   499.7 2216.93   512.7 2214.77   532.3 2207.31   548.6 2196.25
   551.9 2195.42   591.1 2187.19  645.552187.211   662.9 2188.82   679.1 2185.04
   685.4 2184.97   691.7 2185.03   704.2 2188.44     720    2189   749.4 2194.63
  765.262202.578  788.842210.616   798.4 2213.09   814.8 2212.93   821.72216.116
   837.6 2227.56   958.5 2282.32  1027.1 2311.36  1085.9 2330.22    1197 2350.88
#Mann= 7 ,-1 , 0
       0     .12       0  645.55    .016       0   679.1    .045       0
   691.7    .016       0  765.26     .12       0  788.84    .016       0
   821.7     .12       0
#XS Ineff= 2 , 0
                          707.58         2190.43
Permanent Ineff=
       F       F
Bank Sta=679.1,691.7
XS Rating Curve= 0 ,0
Exp/Cntr=0.3,0.1

Type RM Length L Ch R = 1 ,29631.2 ,327.7,310.9,284
XS GIS Cut Line= 4
      2105027.07      182974.944     2104917.695      183624.684
     2104878.633      183636.403     2104846.081      184144.215
#Sta/Elev= 30
       0 2347.85    42.6 2338.62    55.7 2337.52   147.5 2316.82     354 2258.85
   386.8 2250.38   442.5 2239.63   547.4 2207.23   570.4 2201.74   606.4 2186.46
   652.3 2186.05   671.4 2182.43   677.7 2181.49     684 2182.44   690.2  2184.8
  713.282186.917  722.722187.467   738.8 2187.83   768.2 2194.27  790.162203.031
  807.412206.056   820.4 2211.93   843.2    2212  848.552215.118   862.8 2225.17
  1009.5 2289.06  1048.7 2304.08  1133.5 2331.33  1153.1 2332.29  1208.5 2343.27
#Mann= 8 ,-1 , 0
       0     .12       0   671.4    .045       0     684     .12       0
  713.28     .08       0  722.72    .016       0  790.16     .12       0
  807.41    .016       0  848.55     .12       0
#XS Ineff= 2 , 0
                          697.95         2188.21
Permanent Ineff=
       F       F
Bank Sta=671.4,684
XS Rating Curve= 0 ,0
Exp/Cntr=0.3,0.1

Type RM Length L Ch R = 1 ,29320.4 ,367.6,346,329.5
XS GIS Cut Line= 3
     2104767.335      182964.988     2104640.285      183473.197
     2104645.197      184144.697
#Sta/Elev= 30
       0 2346.51    42.6 2337.31    52.4 2336.76    88.4 2325.84   261.9 2267.31
   271.8  2262.4   288.1 2260.07   432.2 2211.14   494.4 2193.29   500.9 2189.34
   507.5 2180.91     514 2176.28   523.8 2175.27  529.522176.148   540.2    2182
   546.8  2183.1   615.6    2183  646.032179.653  710.052180.427  739.592184.539
  771.132187.414  829.232192.363   841.6 2193.79   851.4 2199.91  856.652201.526
   877.6    2201  891.932208.683  1080.7 2273.74  1129.8 2284.74  1195.4 2294.12
#Mann= 10 ,-1 , 0
       0     .12       0     514    .045       0  529.52     .12       0
  646.03     .04       0  710.05     .12       0  739.59     .06       0
  771.13    .016       0  829.23     .12       0  856.65    .016       0
  891.93     .12       0
#XS Ineff= 2 , 0
                          572.98         2186.42
Permanent Ineff=
       F       F
Bank Sta=514,529.52
XS Rating Curve= 0 ,0
Exp/Cntr=0.3,0.1

Type RM Length L Ch R = 1 ,28974.4 ,358.2,373.3,383.2
XS GIS Cut Line= 3
     2103971.988      183150.402     2104403.846      183634.343
     2104555.878      184161.728
#Sta/Elev= 30
       0 2204.01    65.5 2198.81   127.8  2200.3     154 2194.25   216.2 2195.44
   301.4 2241.88   317.3 2245.55   334.1 2251.68  359.332252.258   409.5 2247.85
   445.5 2233.92   461.9 2224.43   497.9 2197.84   504.5 2191.79   514.3  2177.6
  520.472171.739   527.4 2170.68     534 2171.54   573.3 2180.64  598.74 2178.74
   815.2 2178.72  853.972182.195  863.892184.718   880.6 2190.04   916.5 2189.42
  932.41 2196.81     959 2212.43   998.2 2225.66  1141.9 2261.74  1197.5 2272.64
#Mann= 9 ,-1 , 0
       0     .12       0   317.3    .016       0  359.33     .12       0
  520.47    .045       0     534     .12       0  598.74     .04       0
  853.97     .12       0  863.89    .016       0  932.41     .12       0
#XS Ineff= 2 , 0
                          546.13         2179.05
Permanent Ineff=
       F       F
Bank Sta=520.47,534
XS Rating Curve= 0 ,0
Exp/Cntr=0.3,0.1

Type RM Length L Ch R = 1 ,28601.1 ,33.8,29.5,29.1
XS GIS Cut Line= 2
     2103895.733       183162.01     2104255.108      184339.093
#Sta/Elev= 30
       0 2208.13   49.862202.419    78.6 2198.65  124.18 2195.43   183.3 2191.43
   212.8 2187.37   281.5 2185.24   301.1 2188.55     324 2188.31     347 2196.01
   369.9  2199.3   451.7 2203.76   468.1 2201.65   500.8 2193.73  526.272185.321
   546.6 2179.13   556.4 2177.67  696.392169.015  701.392168.343   710.3    2167
   716.8 2168.37   798.7 2168.42  857.172172.969   883.8 2174.18  902.062172.518
   936.1 2177.12   991.8 2178.09  1024.5 2181.71  1191.4 2189.68  1230.7 2199.57
#Mann= 9 ,-1 , 0
       0     .12       0   49.86     .06       0  124.18     .12       0
  526.27    .016       0  696.39     .12       0  701.39    .045       0
   716.8     .12       0  857.17    .016       0  902.06     .12       0
#XS Ineff= 2 , 0
                           721.7         2170.94
Permanent Ineff=
       F       F
Bank Sta=701.39,716.8
XS Rating Curve= 0 ,0
Exp/Cntr=0.3,0.1

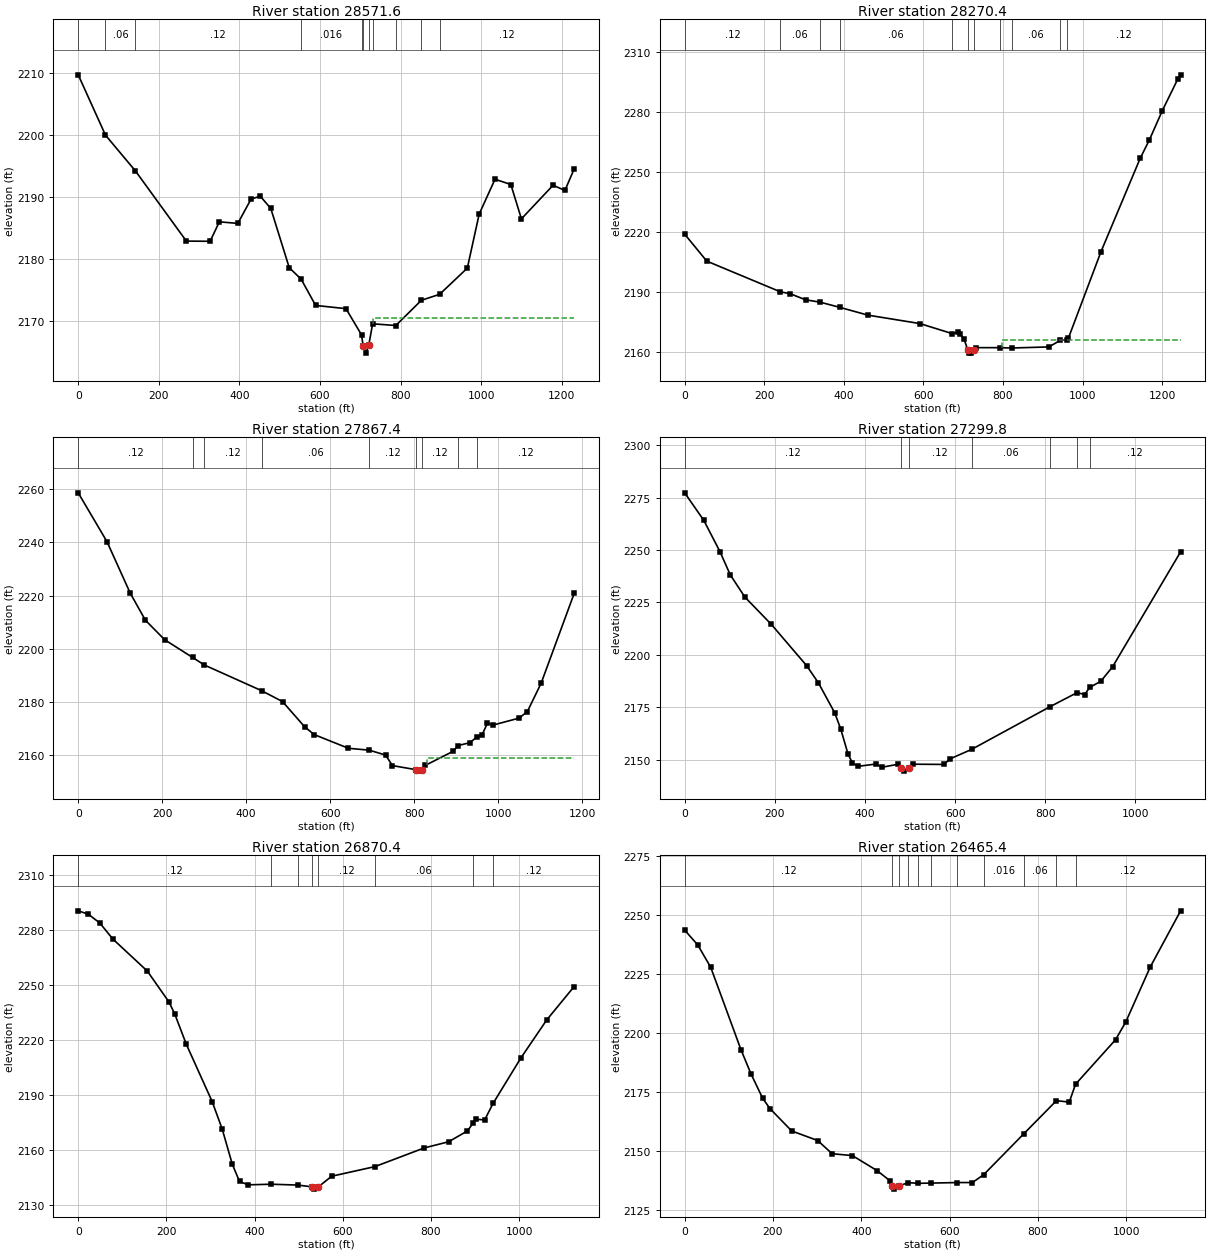
Type RM Length L Ch R = 1 ,28571.6 ,292.7,301.3,310.6
XS GIS Cut Line= 2
     2103870.994      183175.031     2104230.369      184352.114
#Sta/Elev= 30
       0  2209.7   67.632199.964  141.962194.182   268.4 2182.85   327.3 2182.82
   350.2 2185.96   396.1 2185.71   428.8 2189.62   451.7 2190.11   477.9 2188.12
   523.7 2178.55  553.022176.721   589.2 2172.46   664.5 2171.94  703.222167.695
     707 2165.88   713.6 2164.76  720.882166.006   730.62169.498  788.132169.219
  851.54 2173.29  896.882174.258   965.6 2178.49     995 2187.21  1034.3 2192.84
  1073.6 2191.99  1099.8 2186.44  1178.4 2191.87  1207.8 2191.03  1230.7  2194.5
#Mann= 11 ,-1 , 0
       0     .12       0   67.63     .06       0  141.96     .12       0
  553.02    .016       0  703.22     .12       0     707    .045       0
  720.88     .12       0   730.6    .016       0  788.13     .12       0
  851.54    .016       0  896.88     .12       0
#XS Ineff= 2 , 0
                          731.93         2170.48
Permanent Ineff=
       F       F
Bank Sta=707,720.88
XS Rating Curve= 0 ,0
Exp/Cntr=0.3,0.1

Type RM Length L Ch R = 1 ,28270.4 ,383.2,403,414.7
XS GIS Cut Line= 3
     2103845.088      183165.716      2103791.59      183882.293
     2103725.335      184405.816
#Sta/Elev= 30
       0 2218.89    55.5 2205.39  240.412190.023   264.6  2189.1   303.8 2186.02
  339.912184.858  390.372182.209   460.5 2178.34   591.2 2174.12  671.962169.111
   685.9 2169.65   692.4 2168.84   702.2 2166.37   711.1 2161.02   715.3 2159.36
   718.6 2159.32   726.1 2161.06   731.7 2162.07  791.572162.052  821.342161.883
   915.2 2162.43  944.062165.713  960.19 2166.04   964.4 2166.88  1046.3 2210.17
  1144.7 2256.87  1167.6    2266  1200.4 2280.78  1239.7 2296.76  1246.3 2298.67
#Mann= 11 ,-1 , 0
       0     .12       0  240.41     .06       0  339.91    .016       0
  390.37     .06       0  671.96     .12       0   711.1    .045       0
   726.1     .12       0  791.57    .016       0  821.34     .06       0
  944.06    .016       0  960.19     .12       0
#XS Ineff= 2 , 0
                          798.13          2165.8
Permanent Ineff=
       F       F
Bank Sta=711.1,726.1
XS Rating Curve= 0 ,0
Exp/Cntr=0.3,0.1

Type RM Length L Ch R = 1 ,27867.4 ,554,567.5,570.5
XS GIS Cut Line= 3
     2103733.273      183176.443     2103511.919      183766.721
     2103175.547      184202.919
#Sta/Elev= 30
       0 2258.63    68.6 2240.25   124.1 2220.84     160 2210.74   205.8 2203.41
  272.472196.727  300.592193.887  436.592184.257   486.7 2180.14     539 2170.71
   561.8 2167.76   643.5 2162.59  693.08 2161.88   732.1 2160.04   748.4 2156.08
  805.372154.522   810.8    2154  819.122154.494   827.1  2156.2   892.7 2161.43
  904.982163.634   932.1 2164.66  949.912166.814   961.6 2167.55   974.7 2172.04
   987.8 2171.31  1050.1 2173.93  1069.8  2176.4  1102.6 2187.07  1181.2 2220.79
#Mann= 9 ,-1 , 0
       0     .12       0  272.47     .06       0  300.59     .12       0
  436.59     .06       0  693.08     .12       0  805.37    .045       0
  819.12     .12       0  904.98    .016       0  949.91     .12       0
#XS Ineff= 2 , 0
                          830.65          2159.1
Permanent Ineff=
       F       F
Bank Sta=805.37,819.12
XS Rating Curve= 0 ,0
Exp/Cntr=0.3,0.1

Type RM Length L Ch R = 1 ,27299.8 ,448.4,429.5,415.3
XS GIS Cut Line= 3
     2103585.704      183111.339     2103425.113      183337.034
     2102708.968       183742.85
#Sta/Elev= 30
       0 2277.31    42.4 2264.18    78.2  2249.3     101 2238.23   133.6 2227.56
   192.3 2214.53   270.5 2194.87   296.7 2186.63   332.8 2172.37   345.9 2164.82
   362.3 2152.74   372.1 2148.43   385.2 2146.86   424.6 2147.94   437.7  2146.4
   473.8 2147.85   480.3 2146.08   486.9 2144.55  497.672146.102   506.6 2147.86
   575.4 2147.74   588.5 2150.38  636.392154.909  810.762175.323  870.662182.018
     887 2181.08   898.72184.512     923 2187.41   949.3 2194.35  1100.1 2249.17
#Mann= 7 ,-1 , 0
       0     .12       0   480.3    .045       0  497.67     .12       0
  636.39     .06       0  810.76     .12       0  870.66    .016       0
   898.7     .12       0
Bank Sta=480.3,497.67
XS Rating Curve= 0 ,0
Exp/Cntr=0.3,0.1

Type RM Length L Ch R = 1 ,26870.4 ,410.9,404.9,389.2
XS GIS Cut Line= 3
     2103053.077      182679.886     2102942.914      183207.495
      2102645.05      183712.193
#Sta/Elev= 30
       0 2290.66    22.9 2288.82      49 2284.02    78.4 2275.31   156.8 2257.78
   205.8 2240.97   218.9 2234.46     245 2217.98   303.8 2186.63   326.7 2171.56
   349.5 2152.43   365.9 2143.01   385.5 2141.19  438.452141.515  497.562141.054
  530.442140.101   535.7 2138.84  544.782140.105     575 2145.88   673.12151.126
   784.5 2161.28   840.2 2164.68   882.8 2170.57  895.822174.859   902.4 2176.96
     922  2176.6  941.06 2185.59  1003.9  2210.3  1062.8 2231.16    1125 2249.36
#Mann= 8 ,-1 , 0
       0     .12       0  438.45     .06       0  497.56     .12       0
  530.44    .045       0  544.78     .12       0   673.1     .06       0
  895.82    .016       0  941.06     .12       0
Bank Sta=530.44,544.78
XS Rating Curve= 0 ,0
Exp/Cntr=0.3,0.1

Type RM Length L Ch R = 1 ,26465.4 ,291.4,295.1,293.2
XS GIS Cut Line= 2
     2102526.676      182601.357     2102639.523      183718.978
#Sta/Elev= 30
       0 2243.59    29.5 2237.35      59 2227.83   127.7 2192.79   150.6 2182.46
   176.8 2172.25   193.2  2167.9   242.4 2158.44   301.3 2154.37     334 2148.78
   379.9 2147.99   435.6 2141.64     465 2137.32  469.962135.043   474.9 2133.77
  484.952135.055  505.64 2136.52  528.862136.239  558.552136.331  617.922136.563
   651.7 2136.56   677.32139.906  768.11 2157.24  842.012171.286   871.1 2170.67
   885.3 2178.26   975.9 2197.12   998.9 2204.58  1054.5 2227.96  1123.3 2251.78
#Mann= 11 ,-1 , 0
       0     .12       0  469.96    .045       0  484.95     .12       0
  505.64    .016       0  528.86     .12       0  558.55     .06       0
  617.92     .12       0   677.3    .016       0  768.11     .06       0
  842.01    .016       0   885.3     .12       0
Bank Sta=469.96,484.95
XS Rating Curve= 0 ,0
Exp/Cntr=0.3,0.1

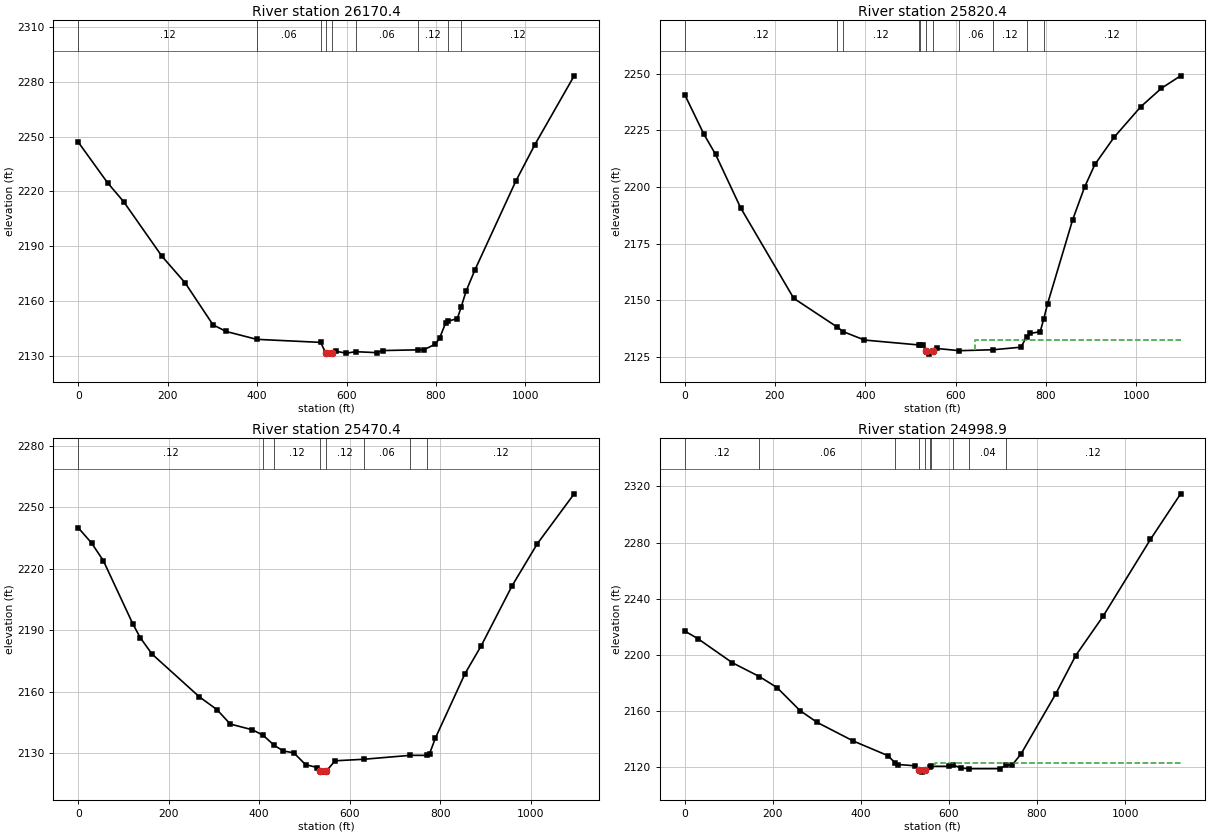
Type RM Length L Ch R = 1 ,26170.4 ,341.8,350,363.2
XS GIS Cut Line= 3
     2102312.684      182564.633     2102287.944      183127.601
     2102365.503      183667.464
#Sta/Elev= 30
       0 2246.97    65.5  2224.7   101.6 2214.32   186.7 2184.57   239.2 2169.79
   301.4 2146.85   330.9 2143.21  399.052138.904  542.052137.231   553.7 2131.29
     557  2130.8  567.962131.265   576.6 2132.32   599.4 2131.36  621.142132.132
     668  2131.6   681.1 2132.76  760.21 2133.15   772.5  2133.2   798.7 2136.24
   808.4 2139.75   821.5 2147.87  827.592148.913   847.6 2150.24  856.292156.606
   867.2 2165.23   886.8 2176.81   978.3 2225.49  1020.7 2245.39  1108.9 2283.25
#Mann= 9 ,-1 , 0
       0     .12       0  399.05     .06       0  542.05     .12       0
   553.7    .045       0  567.96     .12       0  621.14     .06       0
  760.21     .12       0  827.59    .016       0  856.29     .12       0
Bank Sta=553.7,567.96
XS Rating Curve= 0 ,0
Exp/Cntr=0.3,0.1

Type RM Length L Ch R = 1 ,25820.4 ,346.8,350,347.9
XS GIS Cut Line= 3
      2102176.75      182524.053     2101977.159      183031.255
     2101737.603      183529.964
#Sta/Elev= 30
       0  2240.8    42.4 2223.36    68.5 2214.37     124 2190.79   241.5 2150.89
  337.772138.209  351.342136.167   398.2 2132.47  518.982130.301  521.512130.323
   528.7 2130.35   535.3 2127.62   541.8 2126.26  550.842127.623   558.2 2128.76
  608.122127.777  683.312128.198   744.8 2129.32  757.182133.935   764.4 2135.37
   787.3 2136.15   795.32141.878   803.7  2148.5   859.3  2185.6   885.5  2199.9
   908.4 2209.94     951 2221.96  1009.9 2235.39  1055.8 2243.58  1098.3 2249.06
#Mann= 11 ,-1 , 0
       0     .12       0  337.77     .06       0  351.34     .12       0
  518.98     .06       0  521.51     .12       0   535.3    .045       0
  550.84     .12       0  608.12     .06       0  683.31     .12       0
  757.18    .016       0   795.3     .12       0
#XS Ineff= 2 , 0
                          642.39         2132.33
Permanent Ineff=
       F       F
Bank Sta=535.3,550.84
XS Rating Curve= 0 ,0
Exp/Cntr=0.3,0.1

Type RM Length L Ch R = 1 ,25470.4 ,506.8,471.5,442.7
XS GIS Cut Line= 3
     2101920.306      182407.134     2101664.617      182888.374
     2101457.705      183399.362
#Sta/Elev= 30
       0 2240.09    29.4 2232.67    55.5 2224.03   120.7 2193.16     137 2186.46
   163.2  2178.4   267.6 2157.56   306.7 2151.27   336.1 2144.24     385 2141.43
  408.412138.807  433.492133.803   453.6 2131.05   476.4 2130.22   502.5 2124.42
   528.6 2122.99  534.052121.225   541.7 2120.76   548.2  2121.2   567.8  2126.3
  630.682127.032  734.422128.967  770.072128.933   776.6 2129.75   789.6 2137.45
   854.8  2168.8   890.7 2182.43   959.2 2211.82  1014.7 2232.26  1096.2 2256.66
#Mann= 8 ,-1 , 0
       0     .12       0  408.41     .06       0  433.49     .12       0
  534.05    .045       0   548.2     .12       0  630.68     .06       0
  734.42    .016       0  770.07     .12       0
Bank Sta=534.05,548.2
XS Rating Curve= 0 ,0
Exp/Cntr=0.3,0.1

Type RM Length L Ch R = 1 ,24998.9 ,47.9,49.9,43.2
XS GIS Cut Line= 4
     2101229.935      182280.066     2101199.987      182793.087
     2101240.351      182811.316     2101198.685      183377.722
#Sta/Elev= 30
       0 2217.07    29.5 2211.74     108 2194.55  169.732184.663   209.5 2176.89
   261.9 2160.47   301.1 2152.02     383 2138.81   461.5 2128.41  478.142123.175
   484.4 2122.12   523.4  2121.2   532.9 2118.13   539.2  2116.7   546.1 2118.18
  556.512120.693  558.612120.853   600.6 2120.84  608.592122.006   626.7 2119.63
  645.382119.126   714.9 2119.16   729.32121.429   744.2 2121.96   763.8 2129.69
   842.2 2172.15   887.8 2199.57   949.9 2227.51  1057.6 2282.24  1126.1 2314.66
#Mann= 10 ,-1 , 0
       0     .12       0  169.73     .06       0  478.14    .016       0
   532.9    .045       0   546.1    .016       0  556.51     .12       0
  558.61    .016       0  608.59     .12       0  645.38     .04       0
   729.3     .12       0
#XS Ineff= 2 , 0
                          568.49         2123.02
Permanent Ineff=
       F       F
Bank Sta=532.9,546.1
XS Rating Curve= 0 ,0
Exp/Cntr=0.3,0.1