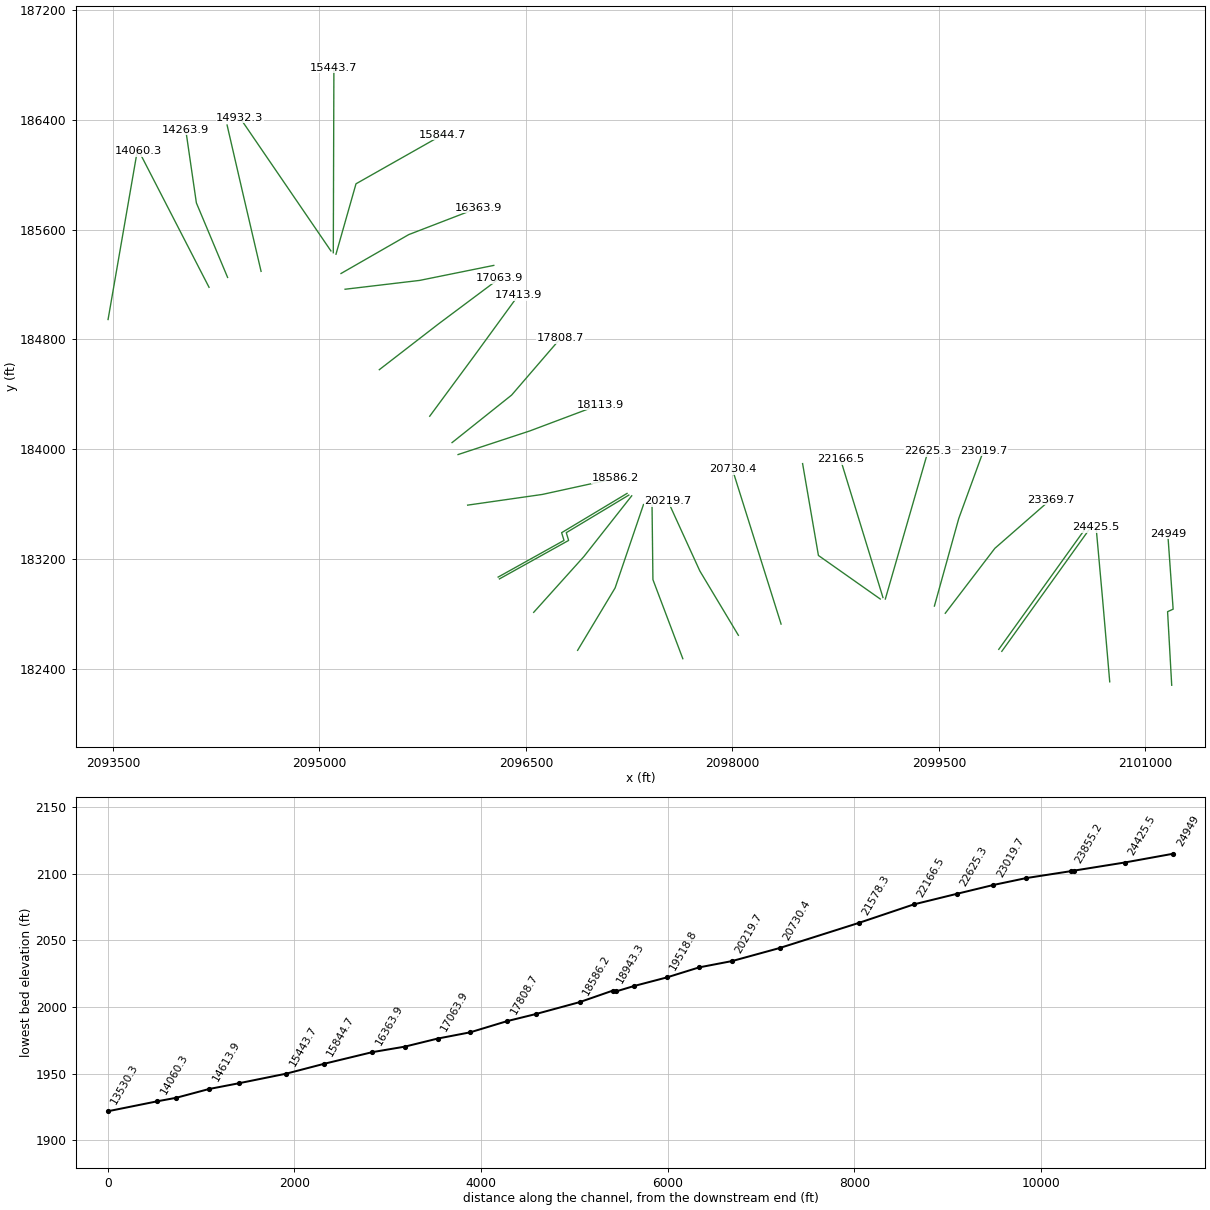
HEC-RAS study DRPLKCR.prj: DRPLKCR

--- DRPLKCR.g01 (geometry) --- (continued)

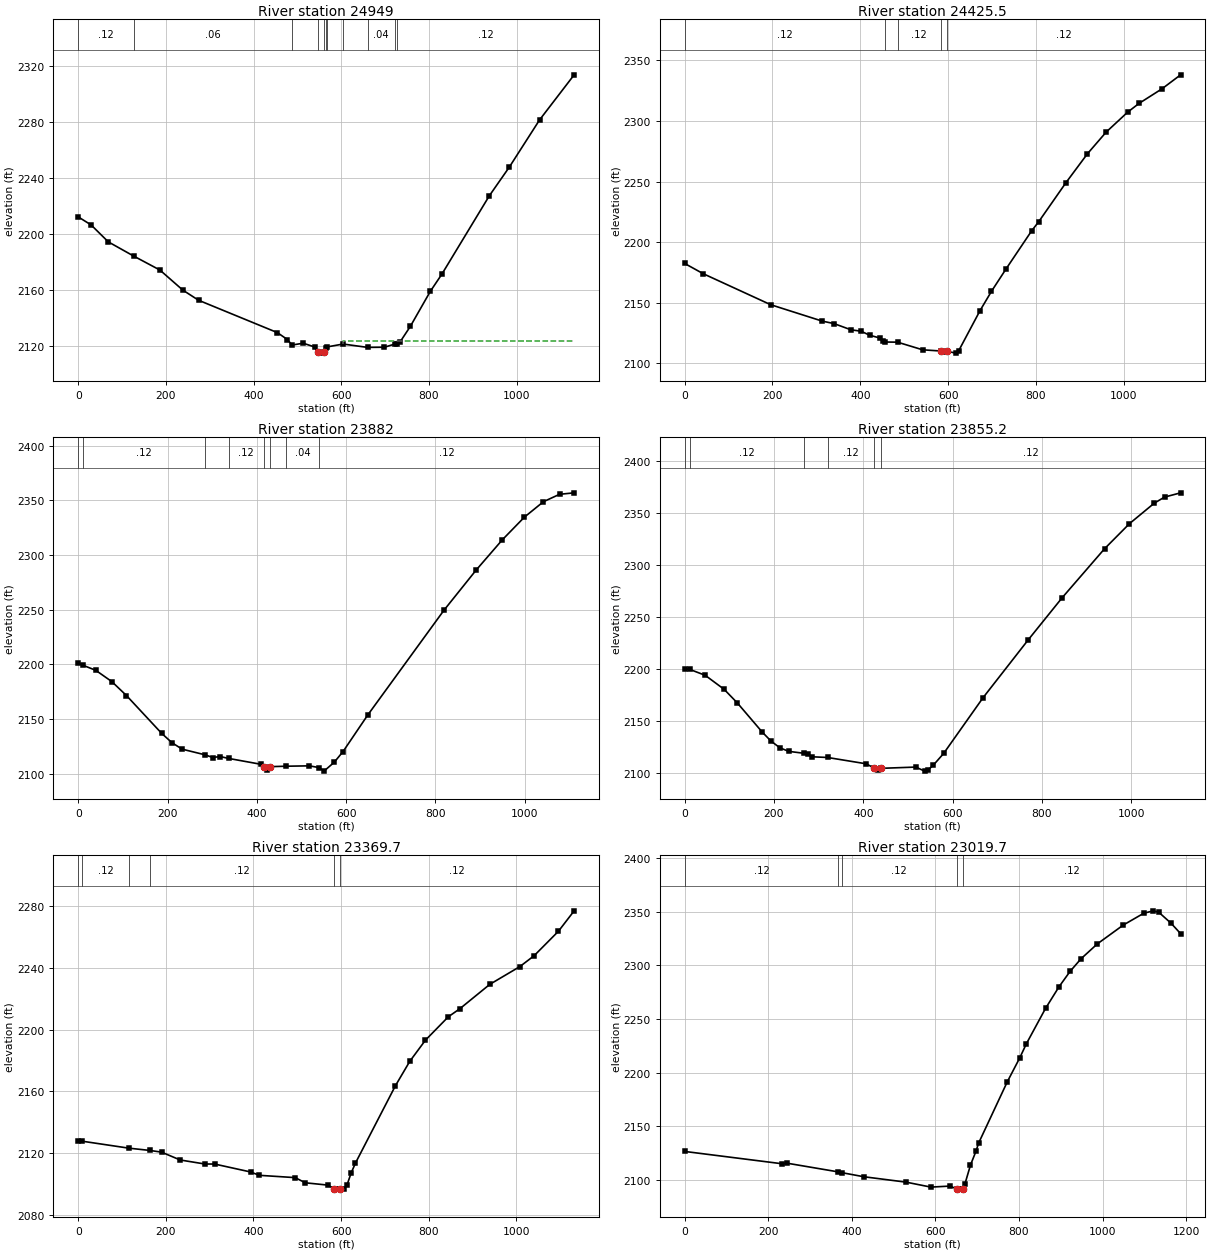
Type RM Length L Ch R = 1 ,24949   ,497.1,523.5,550.4
XS GIS Cut Line= 4
     2101191.306      182284.406     2101161.358      182819.562
     2101201.723      182837.791      2101162.66      183387.271
#Sta/Elev= 30
       0 2212.41    29.4 2206.66    68.6 2194.56   126.72184.376   186.3 2174.43
   238.6 2160.09   274.5 2152.84   454.3 2129.71   477.2 2124.76   487.72120.842
   513.1 2122.14   539.2 2119.46  547.522115.842   551.8 2115.06   561.3 2115.77
  564.822118.631  566.522119.431  604.14 2121.55   659.92119.163   698.3 2119.27
  722.592121.575  727.952121.736   734.4 2123.18   757.4 2134.09   803.2 2159.23
   829.5 2171.49   937.7 2227.47   983.6 2248.11  1052.4 2281.73  1131.2  2313.9
#Mann= 11 ,-1 , 0
       0     .12       0   126.7     .06       0   487.7    .016       0
  547.52    .045       0   561.3    .016       0  564.82     .12       0
  566.52     .06       0  604.14     .12       0   659.9     .04       0
  722.59     .06       0  727.95     .12       0
#XS Ineff= 2 , 0
                          603.26         2123.95
Permanent Ineff=
       F       F
Bank Sta=547.52,561.3
XS Rating Curve= 0 ,0
Exp/Cntr=0.3,0.1

Type RM Length L Ch R = 1 ,24425.5 ,553.9,543.4,525.7
XS GIS Cut Line= 3
     2100741.031      182309.294     2100690.236      182898.172
      2100641.93      183434.511
#Sta/Elev= 30
       0 2182.43    42.4 2173.94   195.9 2148.39   313.5 2134.82   339.6 2132.86
   378.8 2127.67   401.7 2126.52   421.3  2123.2   444.1 2120.93   450.6 2118.36
  456.012117.595  484.882117.462   542.1 2111.15   583.6 2110.17   591.1 2109.29
   597.6 2110.01   617.2 2108.42   623.7  2110.1   672.7 2143.49   698.8 2159.45
   731.4  2177.6   790.2 2209.32   806.5 2216.96   868.5 2249.16   917.4    2273
   959.9 2290.82  1008.8 2307.27  1034.9 2314.55  1087.2  2326.6  1129.6 2338.14
#Mann= 5 ,-1 , 0
       0     .12       0  456.01    .016       0  484.88     .12       0
   583.6    .045       0   597.6     .12       0
Bank Sta=583.6,597.6
XS Rating Curve= 0 ,0
Exp/Cntr=0.3,0.1

Type RM Length L Ch R = 1 ,23882   ,26.9,26.9,26.9
XS GIS Cut Line= 2
     2099957.102      182531.139     2100603.629      183434.177
#Sta/Elev= 30
       0 2201.09   10.822199.154    39.3 2194.55    75.4 2184.19   108.1 2171.45
   186.7 2136.96   209.7 2128.42   232.6 2122.43  283.442117.313   301.4 2114.79
   317.8 2115.68  336.852113.945   409.5 2108.56  415.382106.428   422.6  2103.8
   429.2 2106.41  466.172106.827   517.6 2107.16  539.782105.531   550.4 2102.33
   573.3 2110.44     593  2120.2   648.7 2153.84     819 2249.49   891.1 2286.25
   950.1 2314.09   999.2 2334.69  1041.8  2348.8  1077.9 2355.56  1110.6 2356.92
#Mann= 8 ,-1 , 0
       0     .06       0   10.82     .12       0  283.44    .016       0
  336.85     .12       0  415.38    .045       0   429.2     .12       0
  466.17     .04       0  539.78     .12       0
Bank Sta=415.38,429.2
XS Rating Curve= 0 ,0
Exp/Cntr=0.3,0.1

Type RM Length L Ch R = 1 ,23855.2 ,485.8,485.5,479.9
XS GIS Cut Line= 2
     2099934.966      182545.461     2100581.494        183448.5
#Sta/Elev= 30
       0 2200.53      112199.913    45.9 2194.21    88.5 2180.64   117.9 2167.61
   173.6 2139.59   193.3 2130.91     213 2124.51   232.6 2121.04  268.122119.106
   275.2 2118.67     285  2115.8  320.092115.122   406.2 2109.07  424.822104.864
   432.4  2103.4     439 2104.68   517.6  2105.9   537.3    2102   543.8 2102.67
     557 2107.83   579.9 2118.99   668.3 2172.72   769.9 2228.62   845.2 2268.76
   940.3 2315.96     996 2340.06  1051.6 2359.79  1074.6 2365.64  1110.6 2369.74
#Mann= 6 ,-1 , 0
       0     .06       0      11     .12       0  268.12    .016       0
  320.09     .12       0  424.82    .045       0     439     .12       0
Bank Sta=424.82,439
XS Rating Curve= 0 ,0
Exp/Cntr=0.3,0.1

Type RM Length L Ch R = 1 ,23369.7 ,341.5,350,361.3
XS GIS Cut Line= 3
     2099546.328      182808.171     2099906.273      183280.112
     2100311.175      183634.749
#Sta/Elev= 30
       0 2128.13    8.642127.793   115.6 2123.26  163.452121.792   190.2 2120.68
   232.8  2115.6   288.6 2113.02   311.5 2112.96   393.5 2107.83   413.2 2105.67
   495.2 2104.17   518.1 2100.83   570.6  2099.3   583.7 2096.91   593.5 2096.72
   596.8 2096.75   606.6 2097.05   613.1 2099.14   622.9  2107.2   632.7  2113.6
     724 2163.75   756.6 2179.49   792.5 2193.26   844.7  2208.4   870.8 2213.57
   939.3  2229.4  1007.8 2240.89  1040.4 2247.94  1095.9  2263.8  1131.8 2277.04
#Mann= 6 ,-1 , 0
       0    .016       0    8.64     .12       0   115.6    .016       0
  163.45     .12       0   583.7    .045       0   596.8     .12       0
Bank Sta=583.7,596.8
XS Rating Curve= 0 ,0
Exp/Cntr=0.3,0.1

Type RM Length L Ch R = 1 ,23019.7 ,394.2,394.4,395.8
XS GIS Cut Line= 3
     2099467.289      182860.355     2099644.146      183497.263
     2099824.215      183991.166
#Sta/Elev= 30
       0 2126.66   232.3 2115.23   245.4 2115.69  367.762107.599  375.752106.922
   428.7  2103.1   530.1 2098.05     589 2093.46   634.8  2094.4   651.2 2091.76
   654.5 2091.57  664.822091.911   670.8 2096.64   683.9    2114   696.9 2126.75
   703.4 2134.47     772 2191.54   801.4 2213.51   817.7 2226.98   863.4  2259.8
   896.1  2280.2   922.2  2294.3   948.4 2306.06   987.5 2319.94  1049.6 2337.47
  1098.6 2348.46  1121.4 2350.69  1134.5 2349.34  1163.8 2339.15  1186.7 2329.43
#Mann= 5 ,-1 , 0
       0     .12       0  367.76    .016       0  375.75     .12       0
   651.2    .045       0  664.82     .12       0
Bank Sta=651.2,664.82
XS Rating Curve= 0 ,0
Exp/Cntr=0.3,0.1

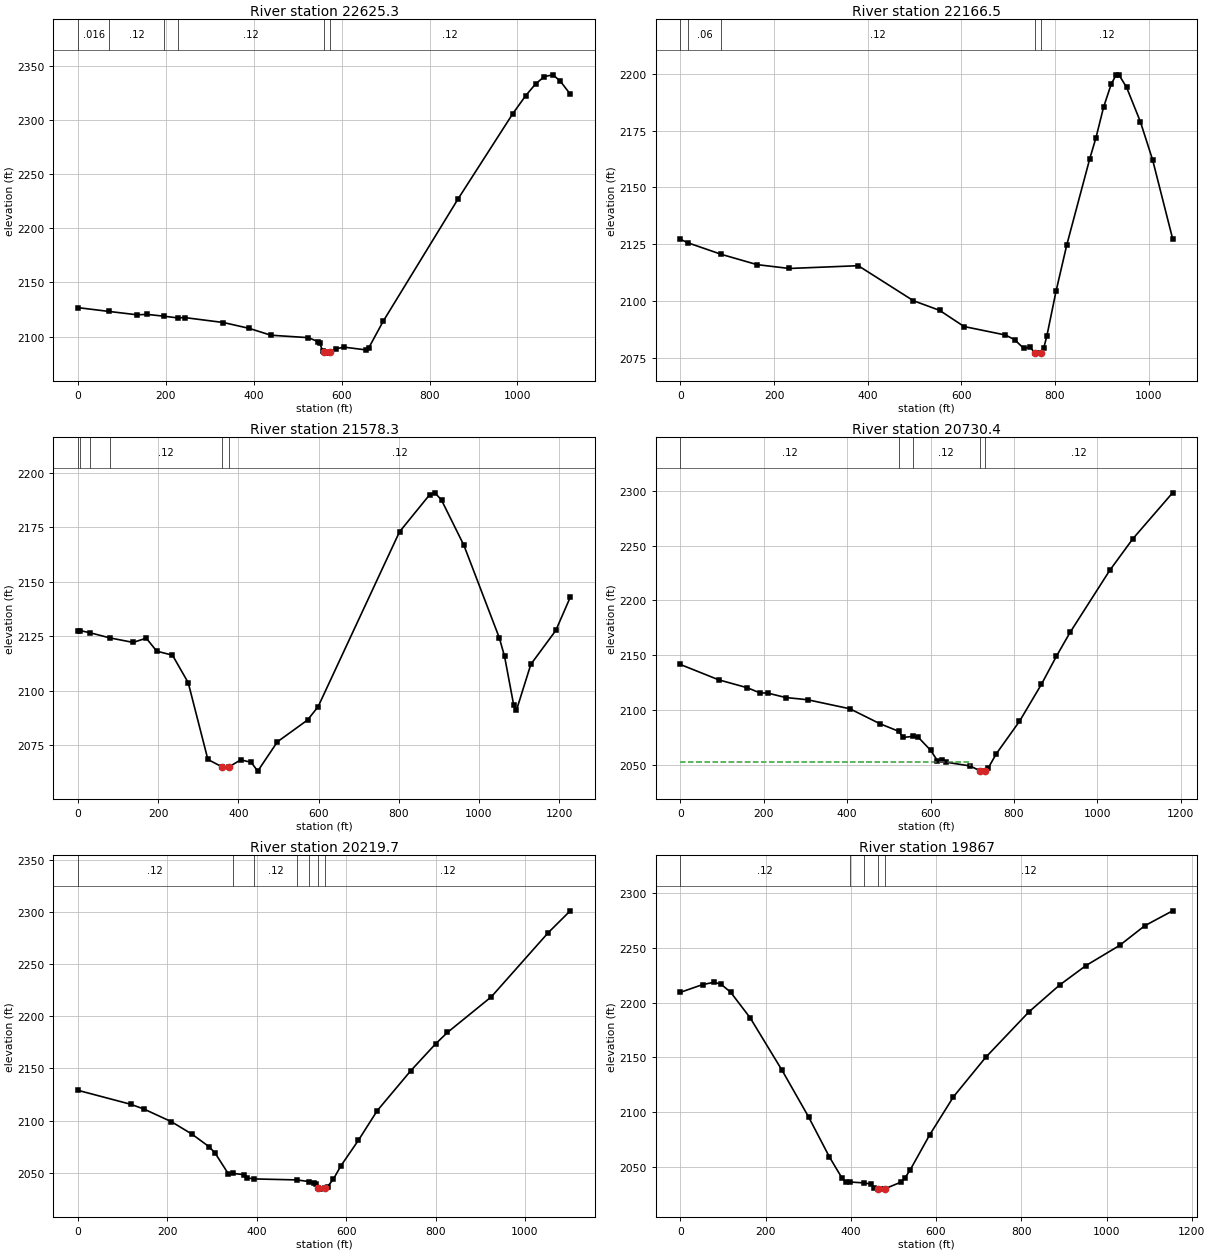
Type RM Length L Ch R = 1 ,22625.3 ,447.7,458.7,471.5
XS GIS Cut Line= 2
     2099110.877      182911.686     2099421.207      183988.075
#Sta/Elev= 30
       0  2126.8   70.672123.289   134.3 2120.21   157.2 2120.57  195.542118.926
  227.272117.316   242.4 2117.66   330.8 2113.09   389.8 2107.67   438.9 2101.38
   524.1 2099.14     547 2095.36   550.3 2093.86   556.8 2086.95  559.122085.677
   563.4 2084.87   573.2 2085.76   586.3 2088.92     606 2090.36   655.1 2087.86
   661.7 2089.74   694.4 2114.17   864.7 2226.88   989.2 2305.45  1018.7 2322.14
  1041.6 2333.14  1061.3  2339.8  1080.9 2341.42  1097.3 2335.72  1120.2 2323.66
#Mann= 6 ,-1 , 0
       0    .016       0   70.67     .12       0  195.54     .06       0
  227.27     .12       0  559.12    .045       0   573.2     .12       0
Bank Sta=559.12,573.2
XS Rating Curve= 0 ,0
Exp/Cntr=0.3,0.1

Type RM Length L Ch R = 1 ,22166.5 ,570.1,588.2,602.7
XS GIS Cut Line= 2
     2099093.516      182922.537     2098785.357      183927.311
#Sta/Elev= 30
       0 2127.11   16.752125.529   87.552120.485   163.7 2115.96   232.5 2114.27
   379.8 2115.49   497.6 2100.06   553.3 2095.84   605.7  2088.7   694.1 2084.96
   713.7 2082.89   733.4 2079.03   746.5 2079.71   756.3 2077.15   759.6 2076.98
  770.112077.186     776 2079.34   782.5  2084.5   802.1 2104.22   825.1 2124.68
   874.2 2162.67   887.3 2171.78   903.6 2185.29     920 2195.51   929.8 2199.29
   936.4 2199.57   952.8 2194.04   982.2 2178.92  1008.4 2162.07    1051 2127.43
#Mann= 5 ,-1 , 0
       0    .016       0   16.75     .06       0   87.55     .12       0
   756.3    .045       0  770.11     .12       0
Bank Sta=756.3,770.11
XS Rating Curve= 0 ,0
Exp/Cntr=0.3,0.1

Type RM Length L Ch R = 1 ,21578.3 ,862.6,847.9,832.3
XS GIS Cut Line= 3
     2099073.985      182911.686     2098624.766      183228.527
     2098509.749      183896.929
#Sta/Elev= 30
       0 2127.54    5.392127.614   29.292126.664   79.152124.281   137.4  2122.2
   170.2 2124.15   196.3 2118.18   235.6 2116.34   274.9  2103.7   323.9 2068.47
   359.9 2064.98   376.3 2065.01   405.7 2068.26   431.9 2067.17   448.3  2063.1
   497.4 2076.57   572.6 2086.57   598.9 2092.68     802 2172.98   877.4 2190.05
   890.5 2190.88   906.8 2187.53   962.6  2166.8    1051 2124.29  1064.1 2115.75
    1087 2093.31  1093.6    2091  1129.6 2112.12  1191.9 2127.69  1227.9 2142.91
#Mann= 6 ,-1 , 0
       0    .016       0    5.39     .06       0   29.29    .016       0
   79.15     .12       0   359.9    .045       0   376.3     .12       0
Bank Sta=359.9,376.3
XS Rating Curve= 0 ,0
Exp/Cntr=0.3,0.1

Type RM Length L Ch R = 1 ,20730.4 ,505.2,510.7,513.3
XS GIS Cut Line= 2
     2098353.499      182729.395     2097999.766      183855.697
#Sta/Elev= 30
       0 2141.52    91.8 2127.55   160.7 2120.28   190.2 2115.71   209.9 2115.39
   252.5  2111.4     305 2109.37   406.6 2101.12   478.8 2087.45  523.372080.639
   534.5 2074.98  556.952075.942   570.6 2075.12   600.1 2063.29   616.5 2053.83
   626.3 2054.37   636.2 2052.46   695.2 2048.96   718.1 2044.61   724.7 2044.26
   731.3 2044.51   737.8 2046.72   757.5 2059.98   813.3  2089.7   865.7  2123.3
   901.8 2148.97   934.6 2170.76  1029.7 2227.33  1085.4 2256.28  1180.5 2298.09
#Mann= 5 ,-1 , 0
       0     .12       0  523.37    .016       0  556.95     .12       0
   718.1    .045       0   731.3     .12       0
#XS Ineff= 2 , 0
          695.25 2052.63
Permanent Ineff=
       F       F
Bank Sta=718.1,731.3
XS Rating Curve= 0 ,0
Exp/Cntr=0.3,0.1

Type RM Length L Ch R = 1 ,20219.7 ,356.4,352.7,350.7
XS GIS Cut Line= 3
     2098043.254      182647.938     2097763.197      183115.903
     2097532.524      183621.706
#Sta/Elev= 30
       0 2129.06   117.6 2115.74     147 2111.25     209    2099   254.7 2087.19
   293.9 2074.85     307 2068.78   336.4 2049.08  345.762049.559   372.3 2048.25
   378.8 2045.21   393.42044.225  489.91 2043.27  517.412041.635     529 2040.14
   532.3 2039.14  537.11  2035.7   542.1 2034.45   551.9 2035.52   558.4 2036.85
   571.5 2044.07   587.9  2056.6   627.1 2081.06   669.6 2109.66   744.8 2147.99
   800.4 2173.71   826.6  2184.5   924.7 2218.61  1052.2  2280.1  1101.3 2300.98
#Mann= 7 ,-1 , 0
       0     .12       0  345.76    .016       0   393.4     .12       0
  489.91     .06       0  517.41     .12       0  537.11    .045       0
   551.9     .12       0
Bank Sta=537.11,551.9
XS Rating Curve= 0 ,0
Exp/Cntr=0.3,0.1

Type RM Length L Ch R = 1 ,19867   ,367.4,348.3,332.2
XS GIS Cut Line= 3
     2097639.523      182477.659     2097422.509      183052.745
     2097415.999       183593.11
#Sta/Elev= 30
       0 2209.47    52.3 2216.56    78.5 2218.59    94.8 2217.05   117.7 2209.67
   163.5 2186.33   238.7 2138.19   300.8 2095.69   349.8 2059.06   379.3 2039.79
   389.1 2035.77  397.052036.242  429.772035.415   447.9 2034.33   454.5 2030.45
   464.3 2030.12   477.4 2029.71   480.6 2030.13   516.6 2035.94   526.4 2039.55
   539.5  2047.4   585.2 2079.38   640.9 2114.08   716.2 2149.96   817.7 2191.51
   889.8 2216.08     952 2233.94  1030.6 2252.28  1089.6 2270.23  1155.1 2283.91
#Mann= 5 ,-1 , 0
       0     .12       0  397.05    .016       0  429.77     .12       0
   464.3    .045       0   480.6     .12       0
Bank Sta=464.3,480.6
XS Rating Curve= 0 ,0
Exp/Cntr=0.3,0.1

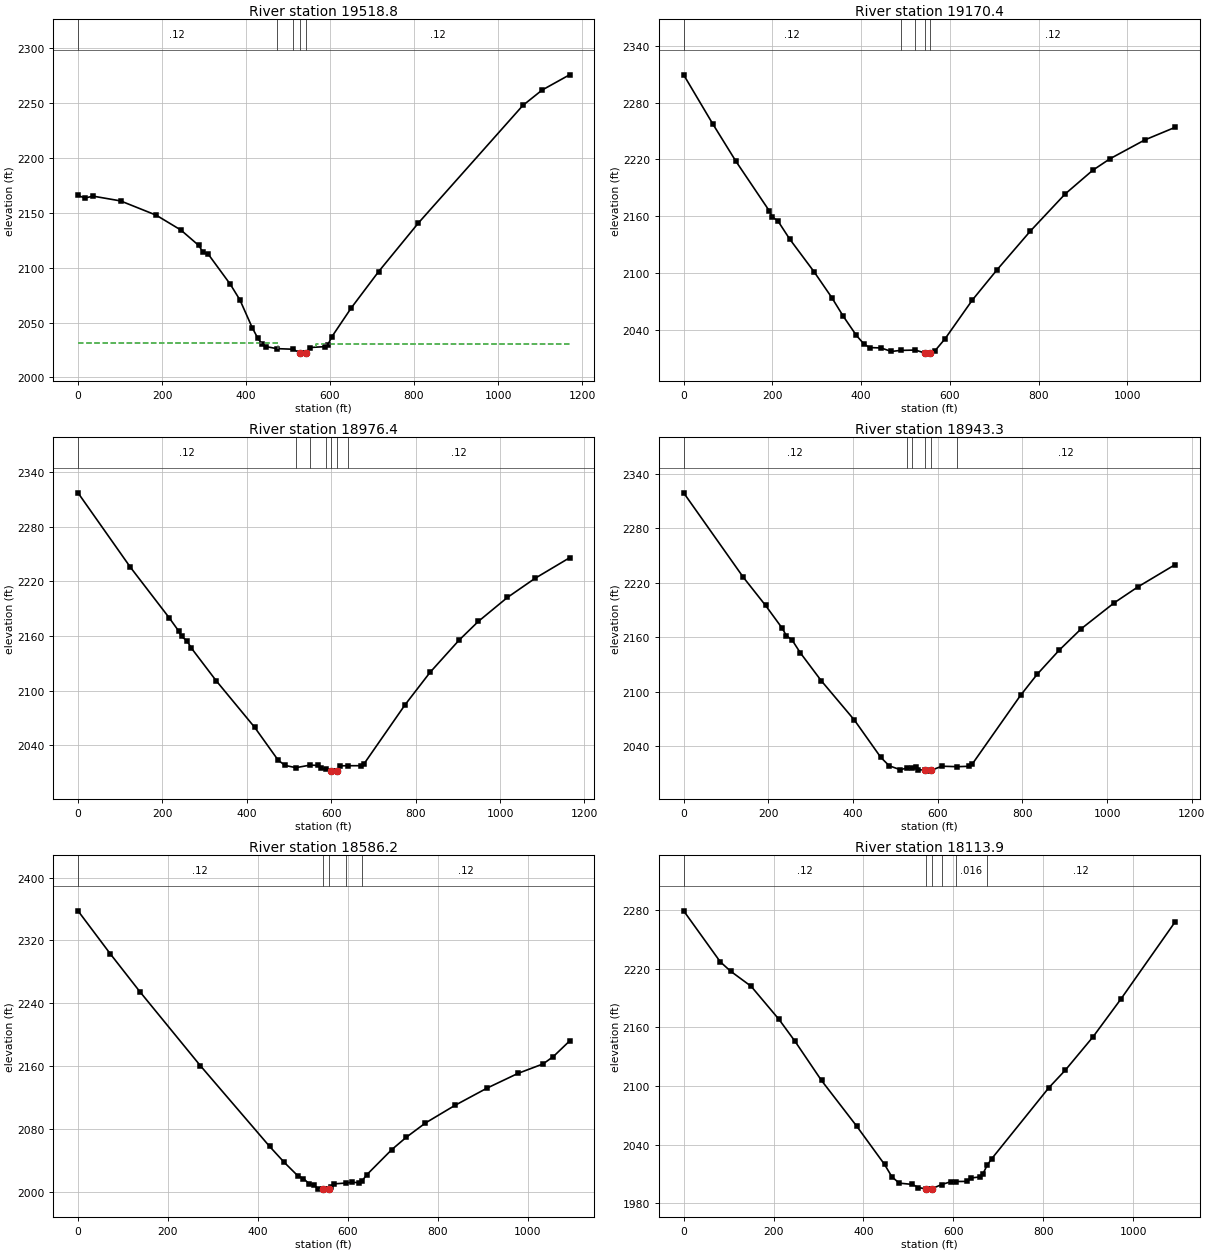
Type RM Length L Ch R = 1 ,19518.8 ,352.9,348.4,340.9
XS GIS Cut Line= 3
     2096875.429      182538.409     2097147.731      182992.248
     2097353.927      183599.017
#Sta/Elev= 30
       0 2165.68    16.3 2163.25    35.9    2165   101.3 2160.67   186.2 2147.67
     245 2134.14   287.5 2120.11   297.3 2114.17   310.4 2112.01   362.6 2084.76
   385.5 2070.54   414.9 2045.19     428 2035.75   437.8 2030.54   447.6 2028.07
  473.142026.227  511.252025.675   529.3 2022.36   539.1 2022.13  542.772022.424
   552.2 2027.25   588.1 2028.04   594.6 2029.64   604.5 2037.13   650.2 2063.12
   715.6 2096.32   810.4 2140.59  1058.9 2247.51  1104.7 2261.52  1170.1 2275.41
#Mann= 5 ,-1 , 0
       0     .12       0  473.14    .016       0  511.25     .12       0
   529.3    .045       0  542.77     .12       0
#XS Ineff= 2 , 0
          476.09 2031.38  567.35         2030.41
Permanent Ineff=
       F       F
Bank Sta=529.3,542.77
XS Rating Curve= 0 ,0
Exp/Cntr=0.3,0.1

Type RM Length L Ch R = 1 ,19170.4 ,168.8,194,216.6
XS GIS Cut Line= 3
     2096556.267      182814.702      2096921.32      183221.246
     2097268.285      183662.383
#Sta/Elev= 30
       0 2309.24    65.4 2257.64   117.8 2218.04     193 2165.75   199.6 2159.51
   212.7 2154.92   238.8 2136.12   294.5 2101.13   333.7 2074.38   359.9 2054.46
   389.3 2034.38   405.7 2025.62   418.8 2021.63     445 2021.18   467.9  2017.5
   488.82018.618  522.162018.974   543.1 2015.93   549.6 2015.74   556.2 2015.94
     566 2018.03   588.8 2030.71   650.8 2071.91   706.3 2103.72   781.3 2144.49
   859.6 2183.56   921.6 2208.51   960.8 2220.75  1039.1 2240.58  1107.6 2253.89
#Mann= 5 ,-1 , 0
       0     .12       0   488.8    .016       0  522.16     .12       0
   543.1    .045       0   556.2     .12       0
Bank Sta=543.1,556.2
XS Rating Curve= 0 ,0
Exp/Cntr=0.3,0.1

Type RM Length L Ch R = 1 ,18976.4 ,33.2,33.1,36.5
XS GIS Cut Line= 4
     2096307.192      183057.843     2096810.056      183338.052
     2096792.869      183394.302     2097247.209      183667.705
#Sta/Elev= 30
       0    2317   124.3 2235.25   215.9 2180.01   238.8 2165.22   245.3 2159.46
   258.4 2154.46   268.2  2146.9   327.1 2111.03   418.7 2059.64   474.3 2023.66
   490.6 2017.91  516.47 2015.45  550.282018.285   569.1 2017.86   575.7 2014.74
  587.762013.612   598.5 2012.22   608.3 2011.65  613.352012.274   621.4 2017.46
  638.86 2017.59   670.5  2017.6     677 2019.12   775.2 2084.58   834.2 2120.01
   902.9 2155.31   948.7 2175.95  1017.4 2202.16  1082.9 2223.16  1164.7  2245.7
#Mann= 7 ,-1 , 0
       0     .12       0  516.47     .06       0  550.28    .016       0
  587.76     .12       0   598.5    .045       0  613.35    .016       0
  638.86     .12       0
Bank Sta=598.5,613.35
XS Rating Curve= 0 ,0
Exp/Cntr=0.3,0.1

Type RM Length L Ch R = 1 ,18943.3 ,396,357.2,315.5
XS GIS Cut Line= 4
     2096298.063      183071.278     2096776.419      183338.052
     2096759.232      183394.302     2097234.478      183680.002
#Sta/Elev= 30
       0 2319.11     141 2225.95   193.5 2194.94   232.9 2169.77   242.7 2161.54
   255.8 2157.11   275.5 2142.76   324.7 2112.15   403.4 2068.51   465.7 2027.45
   485.4 2018.23   511.6 2013.87  527.032015.692  539.152015.722   547.7 2016.46
   554.2 2013.92   570.6 2013.35   580.4 2012.31   583.7 2013.06   609.8 2017.72
  646.762017.213     675 2017.67   681.6 2020.03   795.7 2095.83   834.9 2119.01
     887 2145.64   939.2 2169.31  1017.5 2198.03    1073 2215.43    1161    2240
#Mann= 6 ,-1 , 0
       0     .12       0  527.03     .06       0  539.15    .016       0
   570.6    .045       0   583.7    .016       0  646.76     .12       0
Bank Sta=570.6,583.7
XS Rating Curve= 0 ,0
Exp/Cntr=0.3,0.1

Type RM Length L Ch R = 1 ,18586.2 ,467.8,472.2,475
XS GIS Cut Line= 3
     2096076.461      183594.752     2096618.241      183672.383
      2097151.42      183789.178
#Sta/Elev= 30
       0 2357.63    72.1 2302.71   137.6 2254.78     272 2160.72     426 2058.01
   458.8 2037.58   488.3 2020.86   501.4 2016.96   514.5 2010.23   524.4 2008.94
   534.2 2004.24     544 2003.84   553.8 2003.61  558.352003.822   563.7 2005.88
   570.2 2010.33  595.032011.314   609.4 2012.36   625.8 2011.76  631.042013.551
   642.1 2021.83   697.7 2053.82   730.3 2069.68   772.8 2087.78   838.2 2110.12
   910.1 2132.24   978.7 2150.89  1034.3 2162.88  1057.2 2172.29  1093.1 2191.98
#Mann= 5 ,-1 , 0
       0     .12       0     544    .045       0  558.35     .12       0
  595.03    .016       0  631.04     .12       0
Bank Sta=544,558.35
XS Rating Curve= 0 ,0
Exp/Cntr=0.3,0.1

Type RM Length L Ch R = 1 ,18113.9 ,293.4,305.2,316.5
XS GIS Cut Line= 3
     2096006.834      183962.629     2096527.388      184134.278
     2097037.796      184326.382
#Sta/Elev= 30
       0 2278.92    81.6 2226.75   104.4 2217.27   150.1 2201.83   212.1 2168.01
     248 2145.46   306.7 2105.59     385 2058.92     447 2019.78   463.3 2007.18
   479.6 2000.75     509 1999.41     522 1996.28   538.3 1994.92   541.6 1994.62
   551.4 1994.89  573.911999.318   593.8 2002.09  605.472002.405   629.8 2002.51
   639.6 2006.06   659.2 2007.08   665.7 2010.02  674.932018.862   685.3 2025.66
   812.6  2098.3   848.6 2115.91   910.6 2150.11   972.7 2188.78  1093.5 2267.71
#Mann= 6 ,-1 , 0
       0     .12       0   538.3    .045       0   551.4     .12       0
  573.91     .06       0  605.47    .016       0  674.93     .12       0
Bank Sta=538.3,551.4
XS Rating Curve= 0 ,0
Exp/Cntr=0.3,0.1

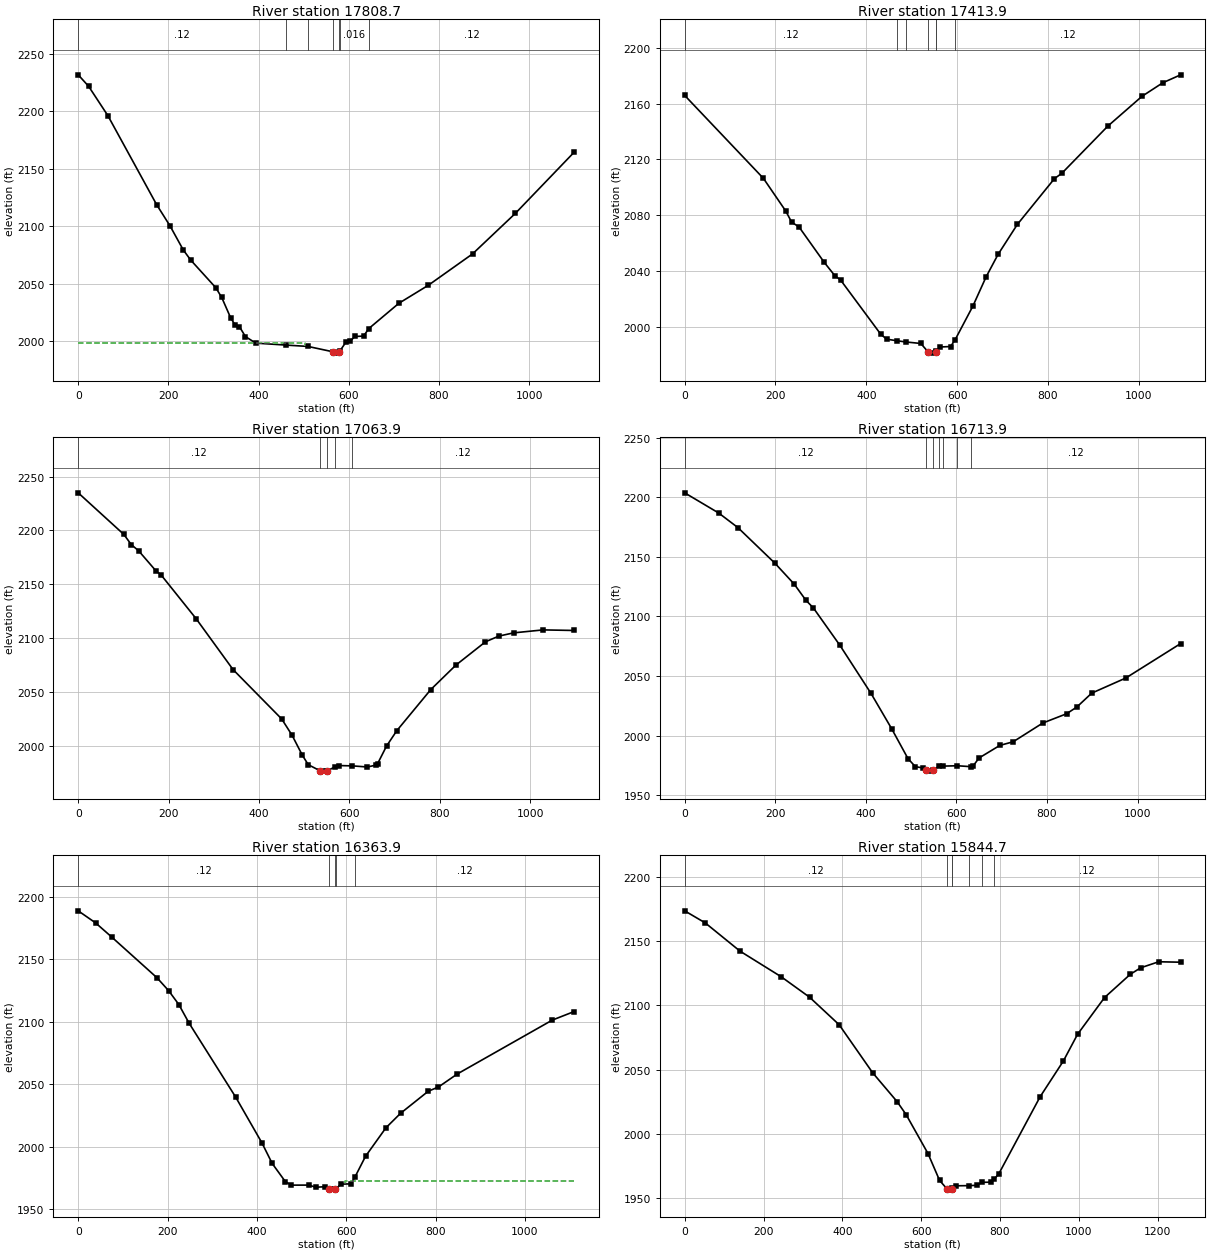
Type RM Length L Ch R = 1 ,17808.7 ,392.3,394.8,396.5
XS GIS Cut Line= 3
     2095963.078      184049.555     2096396.146       184395.61
     2096751.716      184808.891
#Sta/Elev= 30
       0 2231.94      23 2221.98    65.6 2196.46   173.8 2118.81   203.4 2100.36
   232.9 2079.31   249.3 2070.52   305.1 2046.34   318.2 2037.84   337.9 2020.17
   347.7 2013.91   357.5 2012.35   370.7 2003.79   393.6 1998.08   461.11996.354
  509.25 1995.19   564.1 1990.57   573.9 1989.35  578.651990.486  579.341990.793
   593.5 1998.89   603.3  1999.8   613.1 2003.87   632.7  2004.2   644.12010.713
     711 2032.83   776.3 2048.52   874.3 2075.86     969 2111.11  1099.5  2164.5
#Mann= 7 ,-1 , 0
       0     .12       0   461.1    .016       0  509.25     .12       0
   564.1    .045       0  578.65     .12       0  579.34    .016       0
   644.1     .12       0
#XS Ineff= 2 , 0
          502.87  1998.3
Permanent Ineff=
       F       F
Bank Sta=564.1,578.65
XS Rating Curve= 0 ,0
Exp/Cntr=0.3,0.1

Type RM Length L Ch R = 1 ,17413.9 ,355.9,350,342.9
XS GIS Cut Line= 3
     2095800.892      184241.614     2096124.973      184681.383
     2096446.087      185122.912
#Sta/Elev= 30
       0 2165.81   173.4 2106.32   222.4 2082.98   235.5 2074.94   251.9 2071.43
   307.5 2045.99   330.4 2036.64   343.5 2033.34   431.8  1994.5   444.9 1990.96
  468.561989.787  486.841988.979   520.1 1987.88   536.5 1981.66   546.3 1980.96
   552.8 1981.64  554.541982.389   562.6 1985.36   585.5 1985.69  595.481990.473
   634.6 2014.63     664 2035.77   690.1 2051.74   732.6 2073.27   814.4 2106.15
   830.7 2109.98     932 2143.82  1007.2 2165.18    1053 2174.89  1092.2 2180.58
#Mann= 7 ,-1 , 0
       0     .12       0  468.56     .06       0  486.84     .12       0
   536.5    .045       0   552.8     .12       0  554.54    .016       0
  595.48     .12       0
Bank Sta=536.5,552.8
XS Rating Curve= 0 ,0
Exp/Cntr=0.3,0.1

Type RM Length L Ch R = 1 ,17063.9 ,362.1,350,340
XS GIS Cut Line= 3
     2095434.697      184580.102     2095865.522      184913.644
     2096307.943      185244.622
#Sta/Elev= 30
       0 2234.97   101.1 2196.23   117.4 2186.86   133.8 2181.04   172.9 2161.98
   182.7    2159     261  2117.9   342.6 2070.66   450.2 2024.77   473.1 2009.68
   495.9 1991.06     509 1982.24   535.1 1976.59   544.8 1976.24   551.4 1976.68
  567.121979.934   577.5 1981.42  606.521981.119   639.7  1980.1   659.3 1981.85
   662.6 1983.25   682.2  1999.5     705 2013.86   780.2 2052.09   835.8 2074.82
   901.2 2096.48   930.6 2101.76   963.3 2104.77  1028.7 2107.54  1097.4    2107
#Mann= 5 ,-1 , 0
       0     .12       0   535.1    .045       0   551.4     .12       0
  567.12    .016       0  606.52     .12       0
Bank Sta=535.1,551.4
XS Rating Curve= 0 ,0
Exp/Cntr=0.3,0.1

Type RM Length L Ch R = 1 ,16713.9 ,340.2,350,353.5
XS GIS Cut Line= 3
     2095186.036      185165.385     2095727.595      185229.638
     2096266.273      185338.859
#Sta/Elev= 30
       0 2203.63    75.1  2186.7   117.6 2174.44   199.2 2144.61   241.7 2127.13
   267.8 2113.46   284.1 2107.12   342.9 2075.64   411.5 2035.35   457.2 2005.65
   493.1 1980.68   509.4 1973.95   525.8 1972.93  533.87 1970.92   538.8 1970.22
   548.6 1970.81  560.991974.269  570.531974.433  602.331974.725  632.471973.936
     637 1974.63     650 1981.26   695.8 1991.78   725.3 1994.84   790.7 2010.57
   843.1 2018.31     866 2024.02   898.7 2035.63   973.9  2048.3    1095 2077.19
#Mann= 7 ,-1 , 0
       0     .12       0  533.87    .045       0   548.6     .12       0
  560.99     .06       0  570.53    .016       0  602.33     .06       0
  632.47     .12       0
Bank Sta=533.87,548.6
XS Rating Curve= 0 ,0
Exp/Cntr=0.3,0.1

Type RM Length L Ch R = 1 ,16363.9 ,519.2,519.3,522.2
XS GIS Cut Line= 3
     2095156.447      185279.904     2095648.835      185563.052
     2096154.589      185758.258
#Sta/Elev= 30
       0 2188.84    39.2  2179.1    75.1 2167.82   176.3 2135.27   202.4 2124.93
   225.2 2113.84   248.1 2098.96   352.6 2039.64   411.3 2003.03   434.2  1986.6
   463.5 1972.15   476.6 1969.26   515.8 1969.28   532.1 1967.58   551.7 1967.97
   560.5 1966.31   564.7 1966.06   575.5 1966.26  577.791966.459   587.6 1970.03
   610.4  1970.3  619.081975.472   643.1 1992.32   688.8 2015.16   721.5 2026.74
   783.5 2044.42   806.4 2047.83   848.8  2058.3  1061.1 2101.36  1110.1 2108.22
#Mann= 5 ,-1 , 0
       0     .12       0   560.5    .045       0   575.5     .12       0
  577.79    .016       0  619.08     .12       0
#XS Ineff= 2 , 0
                          598.14         1972.47
Permanent Ineff=
       F       F
Bank Sta=560.5,575.5
XS Rating Curve= 0 ,0
Exp/Cntr=0.3,0.1

Type RM Length L Ch R = 1 ,15844.7 ,376.8,401,424.5
XS GIS Cut Line= 3
     2095119.992      185420.367     2095265.391       185932.52
     2095896.902      186290.593
#Sta/Elev= 30
       0 2173.44    52.3 2164.04   140.4 2142.13     245 2122.21   316.8 2106.36
     392 2084.94   476.9 2047.67   538.9 2025.27   561.8 2015.18   617.4  1984.9
   646.8 1964.03   665.3 1957.53   669.7 1957.26  677.931957.587  679.151957.757
   689.4 1959.86  720.381959.965   741.7 1960.22  754.331962.555   777.6 1962.66
  785.091964.831   797.3  1969.3   901.9 2029.02   960.8 2056.75   996.8 2077.48
  1065.4 2106.09  1130.8 2124.16    1157 2129.18  1202.8 2133.87  1258.4 2133.53
#Mann= 7 ,-1 , 0
       0     .12       0   665.3    .045       0  677.93     .12       0
  679.15     .06       0  720.38     .08       0  754.33    .016       0
  785.09     .12       0
Bank Sta=665.3,677.93
XS Rating Curve= 0 ,0
Exp/Cntr=0.3,0.1

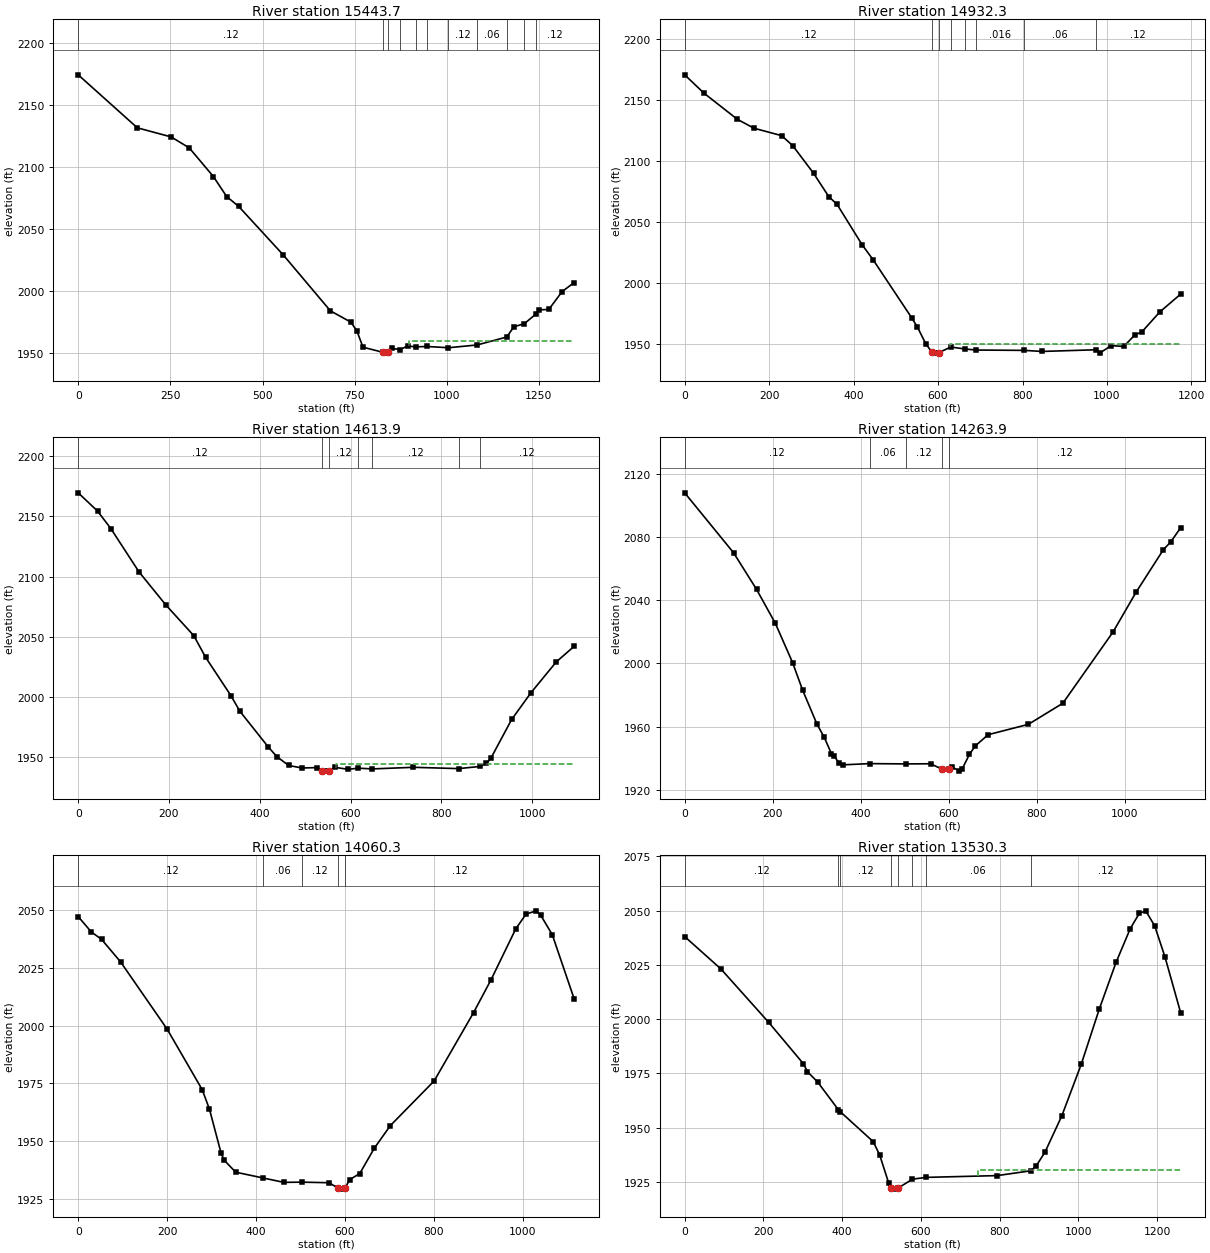
Type RM Length L Ch R = 1 ,15443.7 ,497.5,511.4,524.6
XS GIS Cut Line= 2
     2095100.461      185431.218     2095104.801      186776.704
#Sta/Elev= 30
       0 2174.11   160.4 2131.42   252.1  2124.1   301.2 2115.27   366.7  2092.2
   402.7 2076.09   435.4  2068.1   556.5 2028.96   684.2 1983.99   739.9 1974.87
   756.2  1967.7   772.6 1954.72   826.2 1950.64   834.8 1949.94  839.761950.551
   851.2  1953.9   872.91952.675   893.7 1955.76  915.491954.935  945.021955.324
 1004.231954.277 1082.111956.511 1162.561962.911  1181.8 1971.11 1210.671973.723
 1241.251981.333  1250.6 1984.77  1276.8 1985.13  1312.8  1999.5  1345.5 2006.81
#Mann= 11 ,-1 , 0
       0     .12       0   826.2    .045       0  839.76     .12       0
   872.9    .016       0  915.49     .12       0  945.02     .06       0
 1004.23     .12       0 1082.11     .06       0 1162.56    .016       0
 1210.67     .06       0 1241.25     .12       0
#XS Ineff= 2 , 0
                          896.17         1959.87
Permanent Ineff=
       F       F
Bank Sta=826.2,839.76
XS Rating Curve= 0 ,0
Exp/Cntr=0.3,0.1

Type RM Length L Ch R = 1 ,14932.3 ,326.5,318.3,309.8
XS GIS Cut Line= 2
       2095083.1      185444.239     2094421.207      186414.291
#Sta/Elev= 30
       0 2170.83    45.9 2155.74   124.6 2134.39     164 2127.07   229.6 2120.97
   255.9 2112.75   305.1 2090.18   341.2 2070.99   360.8 2064.65   419.9 2031.68
   446.1 2019.26     538 1971.42   551.1 1964.07   570.8  1950.4  586.081943.216
     597 1942.68   602.1  1943.1  629.981947.688  663.56 1946.09  689.571945.214
  804.081944.931   846.3 1944.06   973.71945.433   984.1 1943.02  1010.3 1948.86
  1039.9 1948.13  1066.1 1957.68  1082.5 1960.02  1125.2 1976.46  1174.4 1991.04
#Mann= 8 ,-1 , 0
       0     .12       0  586.08    .045       0   602.1     .12       0
  629.98    .016       0  663.56     .12       0  689.57    .016       0
  804.08     .06       0   973.7     .12       0
#XS Ineff= 2 , 0
                          627.59         1950.28
Permanent Ineff=
       F       F
Bank Sta=586.08,602.1
XS Rating Curve= 0 ,0
Exp/Cntr=0.3,0.1

Type RM Length L Ch R = 1 ,14613.9 ,345.7,350,347.8
XS GIS Cut Line= 3
     2094575.726      185295.593     2094451.872      185826.773
     2094328.768      186360.113
#Sta/Elev= 30
       0 2169.52    42.5 2154.39    71.8 2139.89   133.9 2103.88   192.7 2076.56
   254.8 2050.83   280.9  2032.8   336.4 2001.14     356 1988.22     418 1958.81
   437.6 1950.43   463.8 1943.08   493.2 1940.98   525.8  1941.3   537.9 1938.67
   545.4 1938.38     552 1938.61   565.1 1941.53   594.6 1939.91  617.281940.829
  648.291940.223   738.8 1941.55  838.151940.475  884.881942.245   899.4 1944.78
   909.2 1949.02   955.1 1981.28   997.7 2003.51  1053.5 2029.13  1092.8 2042.04
#Mann= 7 ,-1 , 0
       0     .12       0   537.9    .045       0     552     .12       0
  617.28    .016       0  648.29     .12       0  838.15     .06       0
  884.88     .12       0
#XS Ineff= 2 , 0
                          567.71         1944.41
Permanent Ineff=
       F       F
Bank Sta=537.9,552
XS Rating Curve= 0 ,0
Exp/Cntr=0.3,0.1

Type RM Length L Ch R = 1 ,14263.9 ,201.8,203.6,210.8
XS GIS Cut Line= 3
     2094332.604      185251.212     2094105.668      185793.821
     2094028.303      186326.796
#Sta/Elev= 30
       0  2107.8   111.1 2069.89   163.4 2046.69   205.8 2025.37   245.1 2000.48
   267.9 1983.06   300.6  1961.5     317 1953.22   333.3 1942.92   339.8 1941.56
   349.6 1937.06   359.4 1935.78  419.951936.561  502.081936.374   558.8 1936.46
   584.9 1933.01  600.081932.999   607.7 1934.39   624.1 1931.81   630.6 1933.29
   646.9 1942.38     660 1947.69   689.3 1954.84   780.7 1961.38   859.1 1974.73
   973.3 2019.86  1025.5 2044.96  1087.6 2071.89  1103.9 2076.62  1126.7 2085.67
#Mann= 5 ,-1 , 0
       0     .12       0  419.95     .06       0  502.08     .12       0
   584.9    .045       0  600.08     .12       0
Bank Sta=584.9,600.08
XS Rating Curve= 0 ,0
Exp/Cntr=0.3,0.1

Type RM Length L Ch R = 1 ,14060.3 ,543.9,530,512.1
XS GIS Cut Line= 2
     2094197.683      185179.482       2093687.7      186171.235
#Sta/Elev= 30
       0 2047.17    29.5 2040.52    52.5 2037.31    95.1 2027.61   200.1  1998.4
   278.8 1972.24   295.2 1963.74   321.4 1944.66     328 1941.74   354.2  1936.5
   416.41933.969   462.5  1932.1  502.451932.194   564.2 1931.94   583.8 1929.64
   590.4 1929.17   600.2 1929.57   610.1 1933.26     633 1935.89   665.8 1946.88
   701.9 1956.68   800.3    1976   888.9 2005.56   928.2 2019.79     984 2041.89
    1007 2048.24  1029.9 2049.67  1039.8 2047.84    1066 2039.34  1115.2 2011.54
#Mann= 5 ,-1 , 0
       0     .12       0   416.4     .06       0  502.45     .12       0
   583.8    .045       0   600.2     .12       0
Bank Sta=583.8,600.2
XS Rating Curve= 0 ,0
Exp/Cntr=0.3,0.1

Type RM Length L Ch R = 1 ,13530.3 ,363.2,371.3,378.4
XS GIS Cut Line= 2
     2093464.176      184945.107      2093679.02      186186.426
#Sta/Elev= 30
       0 2038.04    91.9 2023.14   213.2 1998.55   301.8  1979.4   311.7 1975.81
   337.9 1971.01  390.261958.289  395.451957.317     479 1943.54   495.4 1937.39
   518.3 1924.43   524.9 1922.14   534.8 1921.68   541.3 1922.07  578.451926.259
  612.921927.092   793.9 1927.91  878.661930.117   892.3 1932.19   915.3 1938.74
     958 1955.44  1007.2 1979.12  1053.1 2004.58  1095.7  2026.1  1131.8 2041.68
  1154.8 2048.71  1171.2  2049.9  1194.2 2042.86  1220.4 2028.46  1259.8 2002.99
#Mann= 8 ,-1 , 0
       0     .12       0  390.26     .06       0  395.45     .12       0
   524.9    .045       0   541.3     .12       0  578.45     .08       0
  612.92     .06       0  878.66     .12       0
#XS Ineff= 2 , 0
                           745.6         1930.33
Permanent Ineff=
       F       F
Bank Sta=524.9,541.3
XS Rating Curve= 0 ,0
Exp/Cntr=0.3,0.1