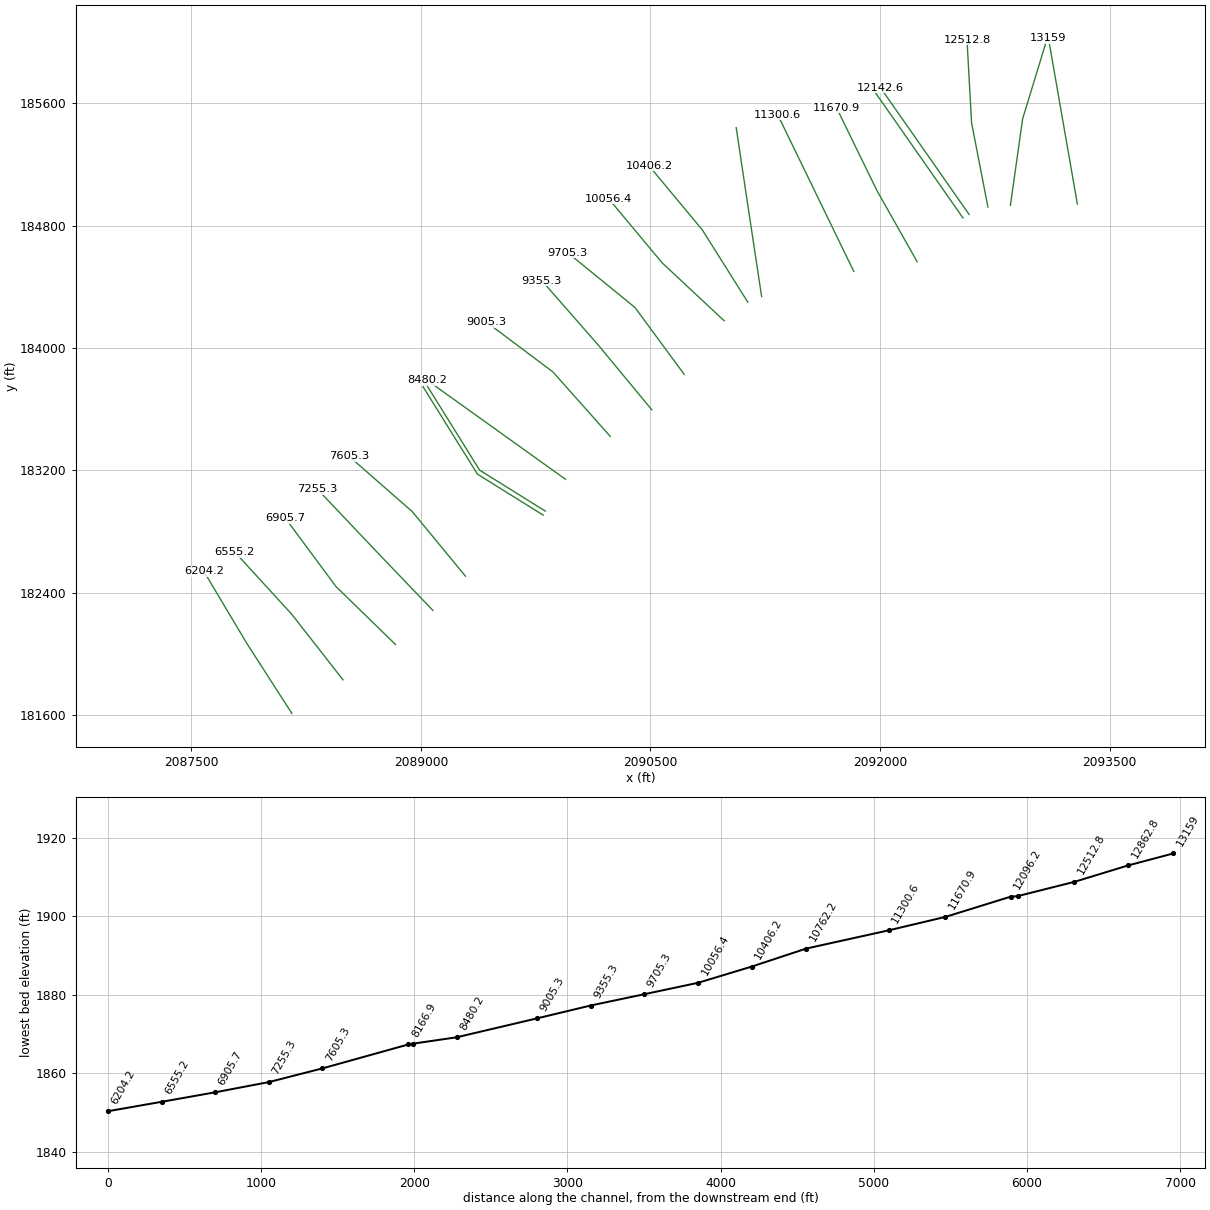
HEC-RAS study DRPLKCR.prj: DRPLKCR

--- DRPLKCR.g01 (geometry) --- (continued)

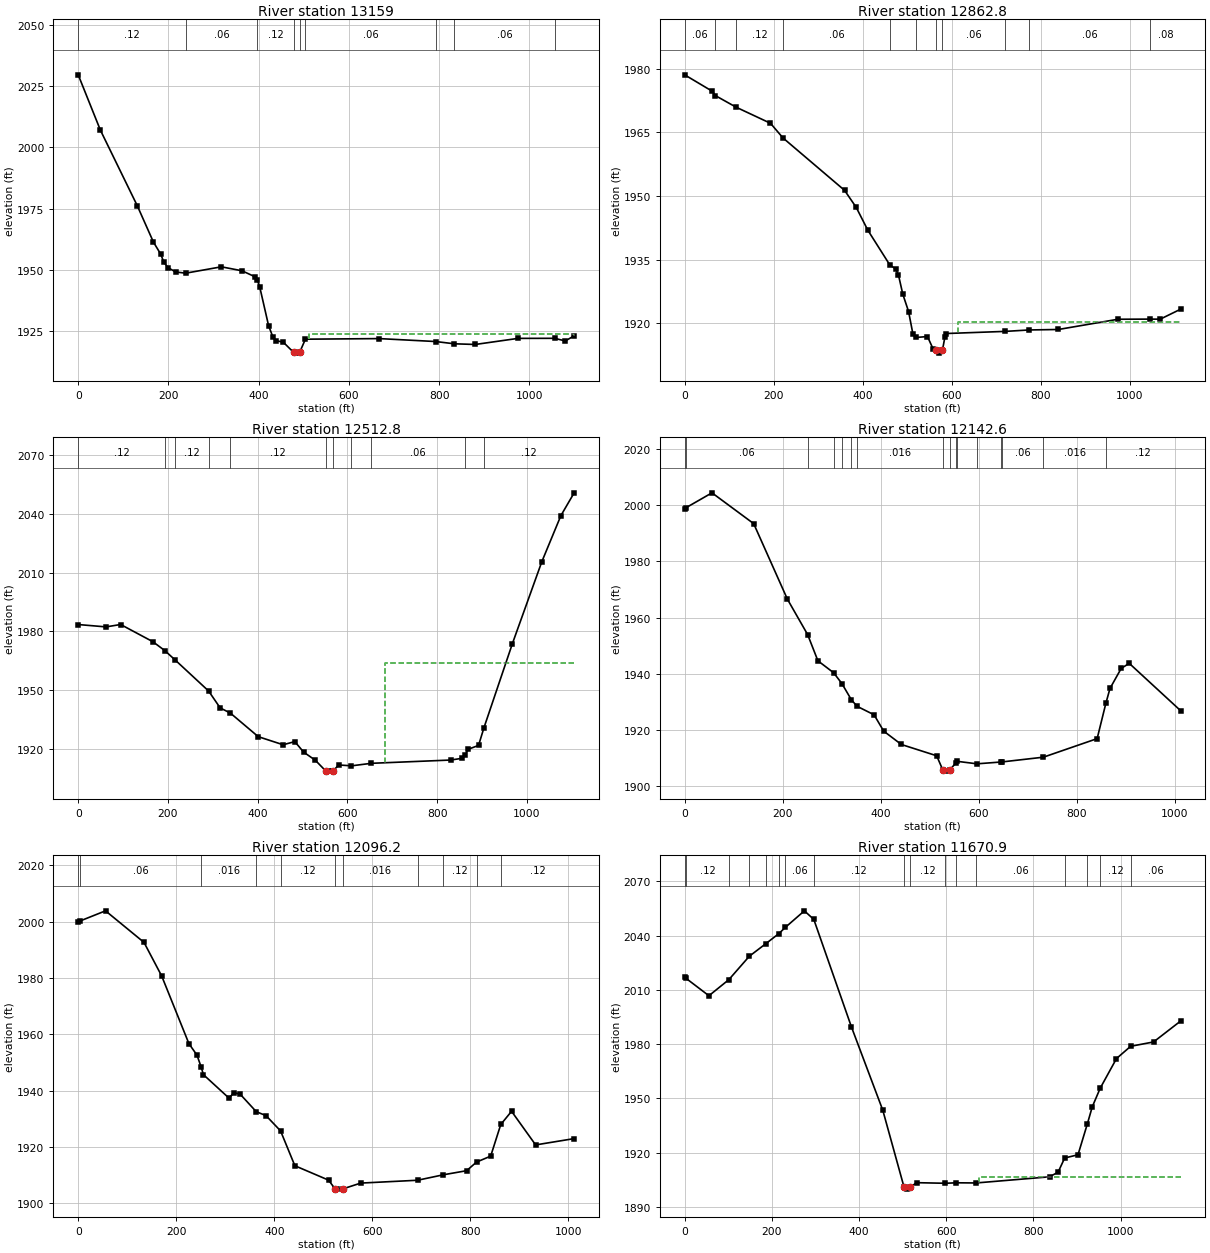
Type RM Length L Ch R = 1 ,13159   ,302.8,296.2,285.4
XS GIS Cut Line= 2
     2093288.395      184940.766     2093099.593      186023.666
#Sta/Elev= 30
       0  2029.5    49.1 2006.97   130.9 1976.15   166.8 1961.29   183.2 1956.32
   189.8 1953.06   199.6 1950.86   215.9 1949.15  238.351948.659   317.3 1951.25
   363.1 1949.63   392.6 1947.12  396.641946.019   402.4 1942.99     422 1927.22
   431.8  1922.5   438.4 1921.19   454.7 1920.49   477.6 1916.34   487.5 1916.07
   490.7 1916.35  503.561921.752   667.4 1921.99  792.171920.797  833.721919.872
     880  1919.6   974.9 1922.08 1055.821922.108  1079.6 1921.04  1099.2 1923.13
#Mann= 9 ,-1 , 0
       0     .12       0  238.35     .06       0  396.64     .12       0
   477.6    .045       0   490.7     .12       0  503.56     .06       0
  792.17    .016       0  833.72     .06       0 1055.82     .08       0
#XS Ineff= 2 , 0
                          511.46         1923.88
Permanent Ineff=
       F       F
Bank Sta=477.6,490.7
XS Rating Curve= 0 ,0
Exp/Cntr=0.3,0.1

Type RM Length L Ch R = 1 ,12862.8 ,342.5,350,357.8
XS GIS Cut Line= 3
     2092850.995      184932.264      2092931.07      185498.166
     2093089.528      186017.026
#Sta/Elev= 30
       0 1978.55      62 1974.68   69.181973.645  115.721970.918   192.7 1967.14
  220.971963.674   359.2 1951.34   385.4 1947.32   411.5 1941.94  460.731933.791
   473.6 1932.85   480.1 1931.48   489.9 1926.92     503 1922.79   512.8 1917.46
  519.941916.686   545.4 1916.91   558.5 1913.89     564 1913.64   571.5    1913
     579 1913.65   584.6  1916.8   587.9 1917.62  720.381918.122  773.791918.456
   839.5 1918.57   973.5 1920.98 1046.121921.013  1068.3    1921  1114.1 1923.35
#Mann= 11 ,-1 , 0
       0     .06       0   69.18    .016       0  115.72     .12       0
  220.97     .06       0  460.73     .12       0  519.94     .06       0
     564    .045       0     579     .06       0  720.38    .016       0
  773.79     .06       0 1046.12     .08       0
#XS Ineff= 2 , 0
                          613.25         1920.25
Permanent Ineff=
       F       F
Bank Sta=564,579
XS Rating Curve= 0 ,0
Exp/Cntr=0.3,0.1

Type RM Length L Ch R = 1 ,12512.8 ,360.5,370.2,382.5
XS GIS Cut Line= 3
     2092704.249      184920.714     2092597.352      185471.546
      2092567.42       186015.03
#Sta/Elev= 30
       0 1983.52      62 1982.32    94.6 1983.54   166.4 1974.77  192.751970.287
  216.411965.388  290.671949.639   316.4 1941.04  339.091938.406   401.3 1926.38
   456.7 1922.26   482.8 1923.86   502.4 1918.52   528.5 1914.36   551.3 1909.01
   564.4 1908.82   567.7 1908.88   580.8 1911.96  609.081911.519  653.351912.802
     830 1914.47   856.2 1915.37  862.231916.969   869.3 1919.97   892.3 1921.92
  904.341930.917   967.7 1973.77  1033.3 2015.52  1075.9 2039.05  1105.4 2050.64
#Mann= 11 ,-1 , 0
       0     .12       0  192.75     .06       0  216.41     .12       0
  290.67    .016       0  339.09     .12       0   551.3    .045       0
   567.7     .12       0  609.08    .016       0  653.35     .06       0
  862.23    .016       0  904.34     .12       0
#XS Ineff= 2 , 0
                          684.83         1964.05
Permanent Ineff=
       F       F
Bank Sta=551.3,567.7
XS Rating Curve= 0 ,0
Exp/Cntr=0.3,0.1

Type RM Length L Ch R = 1 ,12142.6 ,46.4,46.4,46.5
XS GIS Cut Line= 2
     2092581.295      184872.435     2092001.868      185701.863
#Sta/Elev= 30
       0 1998.74    3.431999.246    55.7 2004.49   140.8 1993.49   209.6 1966.52
  250.891953.894   271.8 1944.55  303.981940.273  320.81 1936.41  340.141930.627
  351.68 1928.32   386.4 1925.28     406 1919.46     442 1914.69   514.1 1910.66
  526.841905.504   533.7 1905.18   540.3 1905.54  552.771907.968  556.28 1908.67
  596.421907.788  645.081908.431  647.731908.471  731.69 1910.15   841.5 1916.78
  859.331929.415   867.7 1934.68   890.6 1941.84     907 1943.64  1011.8 1926.75
#Mann= 16 ,-1 , 0
       0     .12       0    3.43     .06       0  250.89    .016       0
  303.98     .06       0  320.81     .12       0  340.14     .06       0
  351.68    .016       0  526.84    .045       0   540.3    .016       0
  552.77     .06       0  556.28    .016       0  596.42     .06       0
  645.08     .12       0  647.73     .06       0  731.69    .016       0
  859.33     .12       0
Bank Sta=526.84,540.3
XS Rating Curve= 0 ,0
Exp/Cntr=0.3,0.1

Type RM Length L Ch R = 1 ,12096.2 ,427.1,425.3,422
XS GIS Cut Line= 2
     2092541.191      184849.779     2091961.764      185679.206
#Sta/Elev= 30
       0 1999.66    3.992000.202    55.7 2003.79   134.2 1992.59   170.3 1980.67
   225.9 1956.64   242.3 1952.58  251.081948.225   255.4 1945.66   307.8  1937.3
   317.6  1939.3   330.7 1938.67  363.261932.513   383.1 1931.12  412.811925.696
     442 1913.33   510.8 1908.22   523.9 1905.14   527.2 1905.03   540.3 1905.14
   576.3 1907.17  692.341908.181  744.781910.116   792.4 1911.57  812.591914.625
   841.5 1916.74   862.11927.972   884.1 1932.65   933.2 1920.72  1011.8 1922.96
#Mann= 11 ,-1 , 0
       0     .12       0    3.99     .06       0  251.08    .016       0
  363.26     .06       0  412.81     .12       0   523.9    .045       0
   540.3    .016       0  692.34     .06       0  744.78     .12       0
  812.59    .016       0   862.1     .12       0
Bank Sta=523.9,540.3
XS Rating Curve= 0 ,0
Exp/Cntr=0.3,0.1

Type RM Length L Ch R = 1 ,11670.9 ,371.6,370.4,368.8
XS GIS Cut Line= 3
     2092241.932      184563.194     2091978.335      185030.139
     2091714.932      185570.872
#Sta/Elev= 30
       0 2016.99    3.512016.369    55.6 2006.82  101.332015.714  148.292028.656
  186.562035.676  216.132041.182  230.722044.573   274.6 2053.77  296.262048.993
   382.5 1989.61   454.5 1943.49     503 1901.18     510 1899.88   516.6 1901.05
   532.9 1903.44   597.91903.117  623.141903.384   668.21903.285     837 1906.69
   856.6 1909.25  871.721917.092   902.3 1918.88   923.41935.683     935 1945.38
  953.231955.689   990.6 1972.09 1023.111978.866  1075.6 1981.26  1137.7 1992.83
#Mann= 17 ,-1 , 0
       0     .06       0    3.51     .12       0  101.33     .06       0
  148.29     .12       0  186.56     .06       0  216.13     .12       0
  230.72     .06       0  296.26     .12       0     503    .045       0
   516.6     .12       0   597.9     .06       0  623.14     .12       0
   668.2     .06       0  871.72    .016       0   923.4     .06       0
  953.23     .12       0 1023.11     .06       0
#XS Ineff= 2 , 0
                          676.23         1906.62
Permanent Ineff=
       F       F
Bank Sta=503,516.6
XS Rating Curve= 0 ,0
Exp/Cntr=0.3,0.1

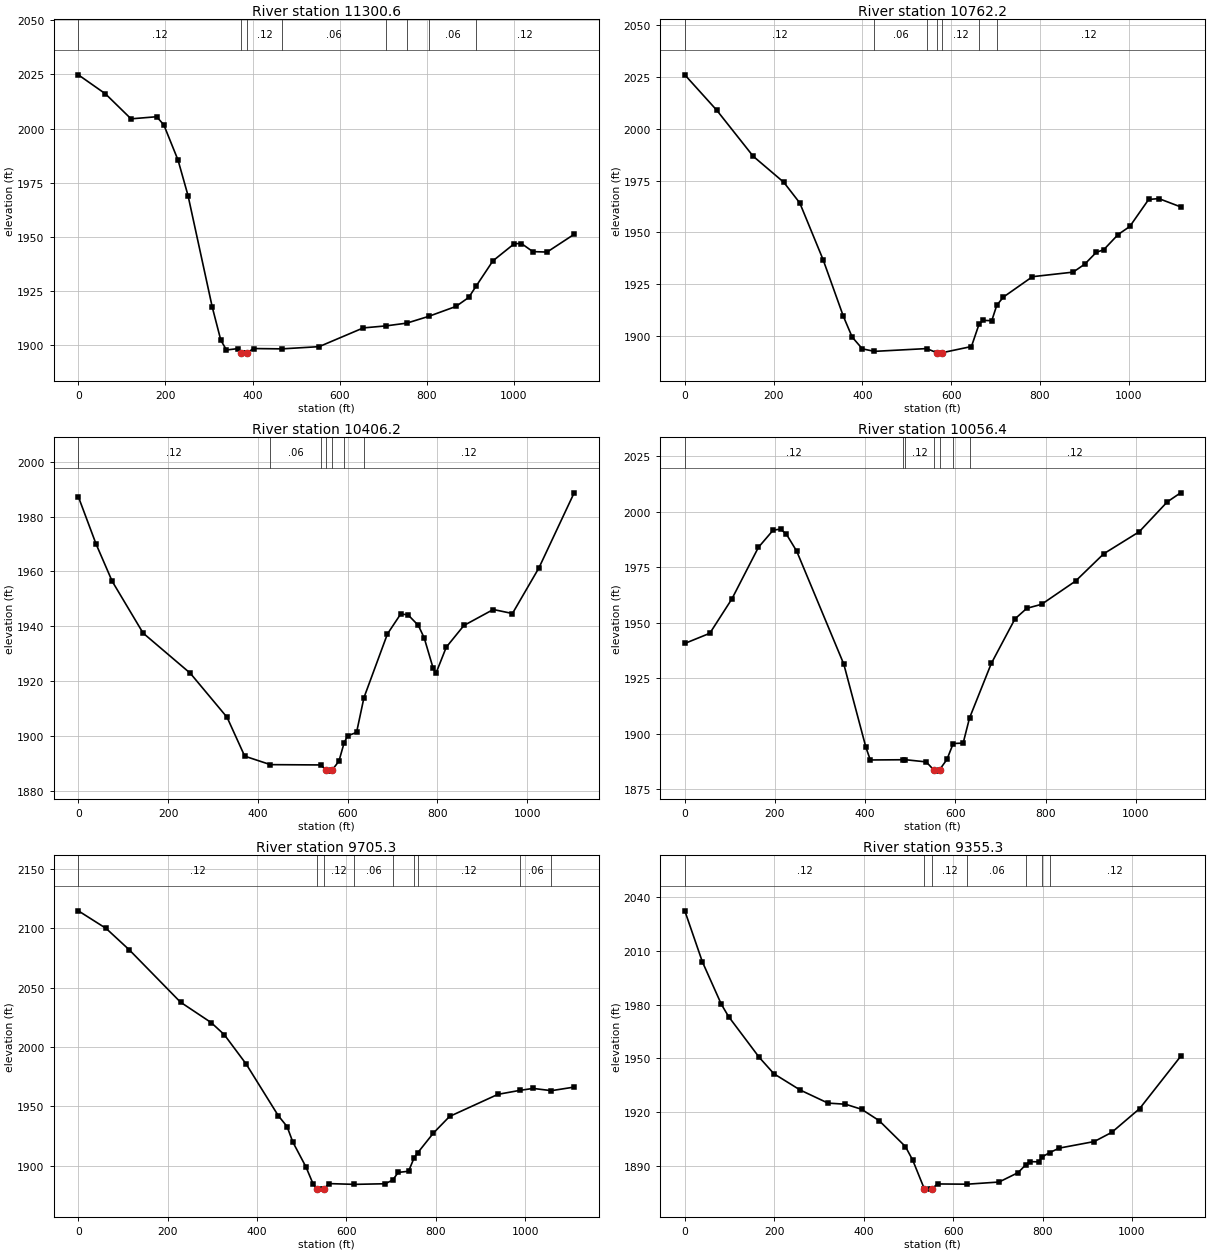
Type RM Length L Ch R = 1 ,11300.6 ,543.4,538.4,530
XS GIS Cut Line= 2
     2091827.891      184500.228     2091330.929      185524.534
#Sta/Elev= 30
       0 2024.82    62.2 2016.06     121 2004.52   179.9 2005.49   196.3 2001.73
     229 1985.44   251.9 1969.11   307.5 1917.69   327.2 1902.37   340.2  1897.9
   366.4 1898.53   374.6  1896.7   382.8 1896.45  388.141896.726   402.4 1898.56
  467.411898.412   552.9 1899.44   654.3 1908.08  705.941909.006  754.211910.287
  804.431913.406     867 1917.98   896.4 1922.13  913.611927.414     952 1939.02
  1001.1 1946.93  1017.4 1947.01  1043.6 1943.27  1076.3 1943.07  1138.5 1951.26
#Mann= 8 ,-1 , 0
       0     .12       0   374.6    .045       0  388.14     .12       0
  467.41     .06       0  705.94     .12       0  754.21    .016       0
  804.43     .06       0  913.61     .12       0
Bank Sta=374.6,388.14
XS Rating Curve= 0 ,0
Exp/Cntr=0.3,0.1

Type RM Length L Ch R = 1 ,10762.2 ,345.3,356,367
XS GIS Cut Line= 3
     2091225.965      184335.653     2091140.824      184899.535
     2091059.902      185439.782
#Sta/Elev= 30
       0 2026.07    72.1 2008.95     154 1986.79   222.9 1974.23   258.9 1964.27
   311.4 1936.92   357.2  1909.5   376.9 1899.55   399.8 1893.87  426.891892.648
  544.751893.996     567 1892.04   576.8  1891.8   580.1 1892.03   645.5 1894.98
  662.621905.748   671.7  1907.6   691.3 1907.45  702.541914.887   717.5 1918.85
   782.9 1928.68   874.5 1930.88   900.6 1934.71   926.8 1940.46   943.2 1941.64
   975.9 1949.03  1002.1  1952.9  1044.6 1965.94  1067.5 1966.36  1116.6 1962.37
#Mann= 7 ,-1 , 0
       0     .12       0  426.89     .06       0  544.75     .12       0
     567    .045       0   580.1     .12       0  662.62    .016       0
  702.54     .12       0
Bank Sta=567,580.1
XS Rating Curve= 0 ,0
Exp/Cntr=0.3,0.1

Type RM Length L Ch R = 1 ,10406.2 ,343.7,349.8,349.6
XS GIS Cut Line= 3
      2091135.64      184299.403     2090838.685      184771.359
     2090489.206      185192.051
#Sta/Elev= 30
       0 1987.24    39.4 1970.02    75.4  1956.4   144.3 1937.51   249.3 1922.89
   331.3 1906.82   370.6 1892.66  427.861889.565  540.141889.454  552.141887.528
   557.6  1887.2   565.1 1887.53   580.5 1890.84  592.231897.611   600.2 1900.09
   619.8 1901.31  636.211913.965   688.6 1937.22   718.1 1944.47   734.4 1944.17
   757.4 1940.32   770.5 1935.74   790.1 1924.86   796.7 1922.88   819.6 1932.37
   858.9 1940.29   924.4 1946.11     967 1944.65  1025.9 1961.24  1104.5 1988.64
#Mann= 7 ,-1 , 0
       0     .12       0  427.86     .06       0  540.14     .12       0
  552.14    .045       0   565.1     .12       0  592.23    .016       0
  636.21     .12       0
Bank Sta=552.14,565.1
XS Rating Curve= 0 ,0
Exp/Cntr=0.3,0.1

Type RM Length L Ch R = 1 ,10056.4 ,354.7,351.1,355.3
XS GIS Cut Line= 3
     2090980.959      184177.646      2090575.63      184556.672
     2090227.024      184974.924
#Sta/Elev= 30
       0  1940.6    55.5 1945.18   104.5 1960.69   163.2 1983.89   195.9 1991.64
   212.2  1992.1   225.2 1989.85   248.1 1982.18   352.6 1931.24   401.5 1893.84
   411.3  1888.1  483.761888.198  488.981888.222   535.4 1887.22   551.7 1883.67
   558.2 1883.07   564.8 1883.68   581.2 1888.31  595.141895.512   617.2  1895.7
  631.271906.969   679.6 1931.58   732.1 1951.66   758.3 1956.43   791.1 1958.23
   866.5 1968.71   928.9    1981  1007.6 1990.92  1069.9  2004.4  1099.4 2008.46
#Mann= 7 ,-1 , 0
       0     .12       0  483.76     .06       0  488.98     .12       0
   551.7    .045       0   564.8     .12       0  595.14    .016       0
  631.27     .12       0
Bank Sta=551.7,564.8
XS Rating Curve= 0 ,0
Exp/Cntr=0.3,0.1

Type RM Length L Ch R = 1 ,9705.3  ,348.6,350,345.6
XS GIS Cut Line= 3
     2090719.912      183827.361     2090398.651      184264.288
     2089958.873      184623.063
#Sta/Elev= 30
       0 2114.78    62.1 2099.96   114.4 2081.76   228.7 2037.78   297.3 2020.57
   326.7 2010.38   375.7 1985.62   447.6 1942.06   467.2 1932.93   480.2 1919.82
   509.6 1898.83     526  1884.1   534.8  1880.4   542.3 1880.16   548.9 1880.38
     562 1884.81  617.851884.177   686.7 1884.69  703.361887.698   716.2 1894.25
   739.2 1895.22  751.961906.811  759.691910.786   794.9 1927.45     831 1941.43
   939.3 1960.07  987.671963.365    1018 1965.06 1059.051963.165  1109.9 1966.19
#Mann= 9 ,-1 , 0
       0     .12       0   534.8    .045       0   548.9     .12       0
  617.85     .06       0  703.36    .016       0  751.96     .08       0
  759.69     .12       0  987.67     .06       0 1059.05     .12       0
Bank Sta=534.8,548.9
XS Rating Curve= 0 ,0
Exp/Cntr=0.3,0.1

Type RM Length L Ch R = 1 ,9355.3  ,349.2,350,354.6
XS GIS Cut Line= 3
     2090508.559      183595.426     2090163.104      184013.566
     2089790.254      184440.049
#Sta/Elev= 30
       0 2032.17    39.2 2003.85    81.7 1980.16      98  1973.3   166.6 1950.57
   199.3 1941.49   258.1 1932.43   320.2 1925.16   359.4 1924.53   395.4 1921.72
   434.6  1915.4   493.4 1900.98   509.7 1893.43   535.8 1877.38   548.9 1877.28
   552.2 1877.45   565.3 1880.16  631.83 1880.03   702.8 1881.23   745.4 1886.46
  762.311890.766   771.6  1892.6   791.2 1892.45  799.411895.245     8161897.577
   837.1 1900.09   915.7 1903.76     955 1908.89  1017.2 1922.09  1108.9 1951.16
#Mann= 7 ,-1 , 0
       0     .12       0   535.8    .045       0   552.2     .12       0
  631.83     .06       0  762.31    .016       0  799.41     .08       0
     816     .12       0
Bank Sta=535.8,552.2
XS Rating Curve= 0 ,0
Exp/Cntr=0.3,0.1

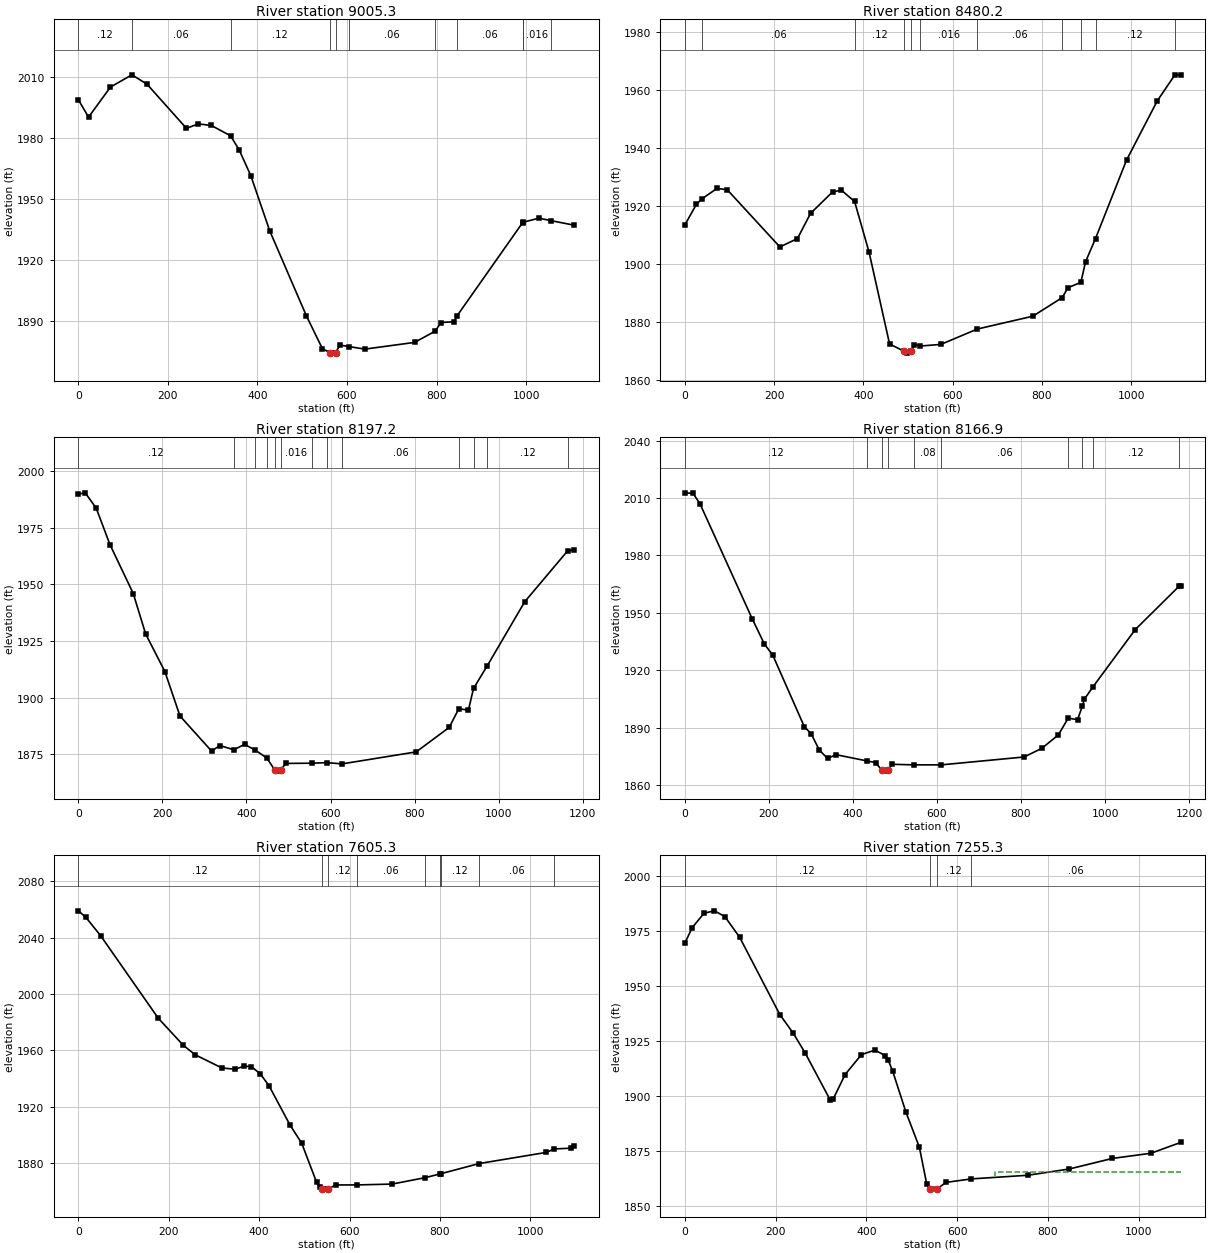
Type RM Length L Ch R = 1 ,9005.3  ,519.8,525.2,525.6
XS GIS Cut Line= 3
     2090237.309      183421.522     2089862.269      183843.546
     2089428.093      184169.178
#Sta/Elev= 30
       0 1999.06    22.8 1990.42    71.8 2005.28  119.652011.307   153.4 2006.69
   241.5 1984.88   267.6 1987.11     297 1986.32  339.931981.234     359 1974.35
   385.1 1961.62   427.5  1934.3   509.1  1892.5     545 1876.22   561.3 1874.28
   567.9    1874   574.4 1874.21   584.2 1877.97  604.441877.229   639.8 1875.98
   750.9 1879.29  797.171884.858   809.8  1889.1   839.2  1889.5  845.251892.223
  991.981938.308  993.421938.591  1028.8 1940.59 1054.691939.408  1107.3 1937.12
#Mann= 11 ,-1 , 0
       0     .12       0  119.65     .06       0  339.93     .12       0
   561.3    .045       0   574.4     .12       0  604.44     .06       0
  797.17    .016       0  845.25     .06       0  991.98     .12       0
  993.42    .016       0 1054.69     .06       0
Bank Sta=561.3,574.4
XS Rating Curve= 0 ,0
Exp/Cntr=0.3,0.1

Type RM Length L Ch R = 1 ,8480.2  ,281.2,283,284.2
XS GIS Cut Line= 2
     2089944.211      183141.721     2089041.433      183788.423
#Sta/Elev= 30
       0 1913.32    26.2 1920.49   38.991922.404    72.1 1925.92      95 1925.48
   212.9 1905.77   252.2 1908.63   281.7 1917.33   330.9 1924.72   350.5 1925.31
  380.271921.441   412.8  1903.9   458.6 1872.34   491.4 1869.78   497.9 1869.17
  506.77 1869.82   514.3 1872.14  527.221871.613   573.3 1872.17  655.491877.483
   779.6  1881.9  845.29  1888.3   858.3 1891.73  887.011893.548   897.6 1900.66
  919.851908.644   989.3 1935.67  1058.1 1956.07 1097.491965.025  1110.5 1965.07
#Mann= 11 ,-1 , 0
       0     .12       0   38.99     .06       0  380.27     .12       0
   491.4    .045       0  506.77     .12       0  527.22    .016       0
  655.49     .06       0  845.29    .016       0  887.01     .08       0
  919.85     .12       0 1097.49     .06       0
Bank Sta=491.4,506.77
XS Rating Curve= 0 ,0
Exp/Cntr=0.3,0.1

Type RM Length L Ch R = 1 ,8197.2  ,30.2,30.3,30.2
XS GIS Cut Line= 3
     2089813.326      182933.113     2089383.639      183201.342
      2089028.17      183772.956
#Sta/Elev= 30
       0 1989.85    16.3  1990.4    42.5 1983.66    75.2 1967.57   130.7 1945.94
   160.1 1928.14   205.9 1911.52   241.8 1891.91     317 1876.41   336.6 1878.86
   370.11876.978   395.4 1879.38  421.161876.816  448.621873.332   467.3 1868.06
   477.1 1867.56  481.651868.038   493.5 1870.96  555.131871.063  592.42  1871.3
  627.211870.751   803.9 1876.05   882.3 1886.85   905.31895.087   928.1  1894.5
  940.251904.049  972.911914.043    1062  1942.3 1164.171964.783  1179.7 1965.26
#Mann= 13 ,-1 , 0
       0     .12       0   370.1    .016       0  421.16     .06       0
  448.62    .016       0   467.3    .045       0  481.65    .016       0
  555.13     .08       0  592.42     .12       0  627.21     .06       0
   905.3    .016       0  940.25     .08       0  972.91     .12       0
 1164.17     .06       0
Bank Sta=467.3,481.65
XS Rating Curve= 0 ,0
Exp/Cntr=0.3,0.1

Type RM Length L Ch R = 1 ,8166.9  ,567.7,561.6,556.9
XS GIS Cut Line= 3
     2089799.003      182907.071     2089369.316        183175.3
     2089013.847      183746.915
#Sta/Elev= 30
       0 2012.69    19.6 2012.42      36 2007.04   160.1 1947.04   189.5 1933.67
   209.2 1927.98   284.3 1890.61   300.6 1886.86   320.3 1878.27   339.9 1873.96
   359.5 1875.97  433.981872.658   454.2 1871.78  468.041868.039   480.2 1867.36
   483.7 1868.01   493.5 1870.93  544.881870.629  610.131870.628   807.2 1874.74
   849.6 1879.28   888.8 1886.28  912.251895.032   934.6 1894.23  945.781901.314
   950.9    1905  970.921911.315  1071.8 1941.29 1176.431964.002  1179.7 1964.25
#Mann= 10 ,-1 , 0
       0     .12       0  433.98    .016       0  468.04    .045       0
   483.7    .016       0  544.88     .08       0  610.13     .06       0
  912.25    .016       0  945.78     .08       0  970.92     .12       0
 1176.43     .06       0
Bank Sta=468.04,483.7
XS Rating Curve= 0 ,0
Exp/Cntr=0.3,0.1

Type RM Length L Ch R = 1 ,7605.3  ,348.2,350,347.6
XS GIS Cut Line= 3
     2089291.561      182507.775     2088944.149      182929.757
     2088530.224      183292.229
#Sta/Elev= 30
       0 2059.14    16.4 2054.61    49.1 2041.56   176.7 1982.82   232.4 1963.46
   258.6 1956.77   317.5 1947.42   346.9 1946.51   366.6 1948.69   382.9 1948.34
   402.6 1943.23   422.2 1934.54     468 1906.96   494.2 1893.82     527 1866.14
   533.5 1862.43   539.1 1861.47   546.6 1861.25   553.1 1861.47   569.5 1864.22
  616.751864.244     694 1864.84  767.611869.427  800.071872.071  801.561872.178
  887.031879.467  1034.6 1887.33 1052.681889.814  1090.2 1890.37  1096.8 1891.75
#Mann= 9 ,-1 , 0
       0     .12       0   539.1    .045       0   553.1     .12       0
  616.75     .06       0  767.61     .12       0  800.07     .06       0
  801.56     .12       0  887.03     .06       0 1052.68    .016       0
Bank Sta=539.1,553.1
XS Rating Curve= 0 ,0
Exp/Cntr=0.3,0.1

Type RM Length L Ch R = 1 ,7255.3  ,349.2,349.6,346.8
XS GIS Cut Line= 3
     2089078.742      182283.934     2088701.315      182678.489
     2088325.807      183074.857
#Sta/Elev= 30
       0 1969.36    16.4 1976.43    42.5 1982.99    65.4 1984.05    88.3 1981.42
     121 1971.98   209.2    1937   238.7 1928.56   264.8 1919.65   320.4 1898.14
     327 1898.72   353.1 1909.76   389.1 1918.81   418.5 1920.82   441.4 1918.39
   447.9 1916.35   457.7 1911.36   487.2  1892.6   516.6 1876.78   532.9 1860.02
   539.5 1857.85   542.7 1857.75   555.8 1857.87   575.4 1860.81  631.041862.392
   755.2 1864.04   846.8 1866.89   941.6 1871.68  1026.6 1874.03    1092 1878.93
#Mann= 4 ,-1 , 0
       0     .12       0   539.5    .045       0   555.8     .12       0
  631.04     .06       0
#XS Ineff= 2 , 0
                          682.55         1865.54
Permanent Ineff=
       F       F
Bank Sta=539.5,555.8
XS Rating Curve= 0 ,0
Exp/Cntr=0.3,0.1

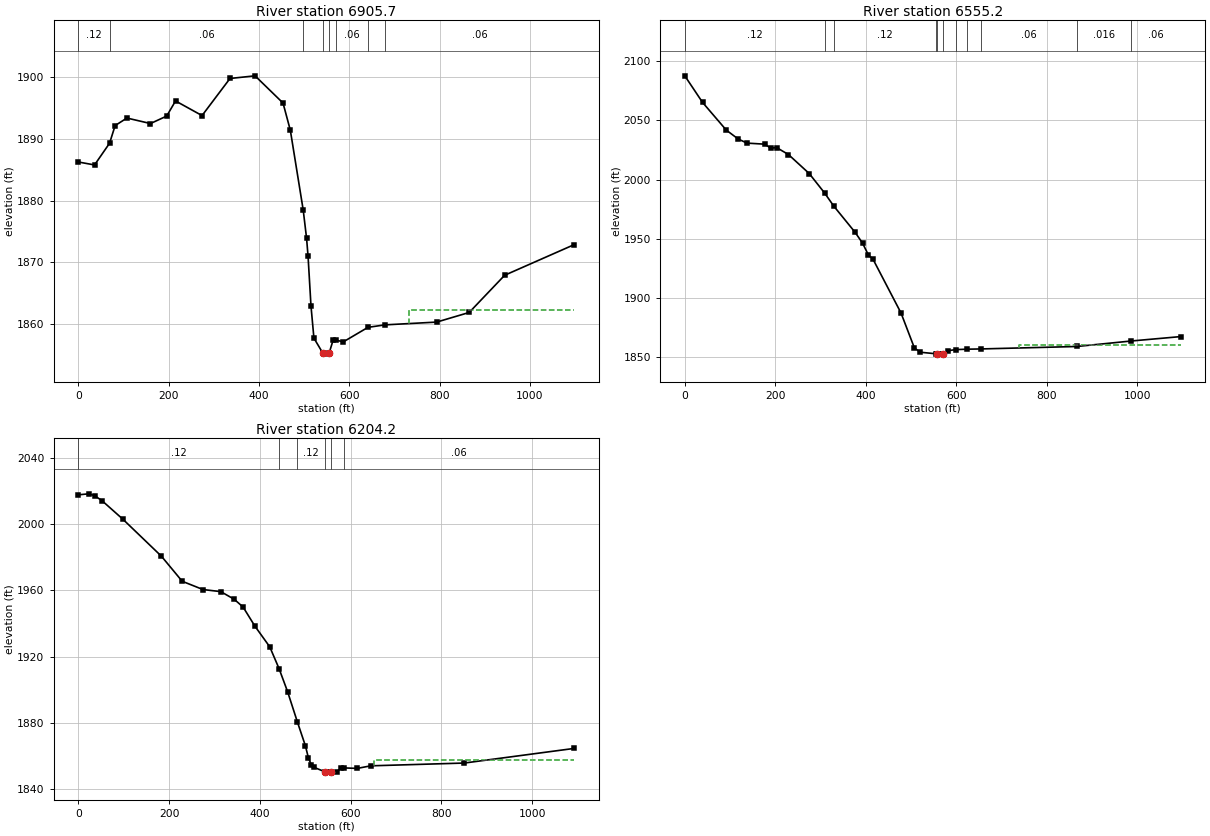
Type RM Length L Ch R = 1 ,6905.7  ,351.3,350.4,352.3
XS GIS Cut Line= 3
     2088834.842      182060.927     2088444.799      182441.097
     2088115.583      182886.106
#Sta/Elev= 30
       0 1886.28    35.9  1885.8   69.18 1889.32    81.5 1892.18   107.6  1893.4
   159.8 1892.51   195.7 1893.72   215.3 1896.17     274  1893.8   335.9 1899.81
   391.4 1900.24   453.4 1895.83   469.6  1891.4  498.091878.495   505.5 1873.94
   508.8 1871.03   515.3 1862.95   521.8 1857.74   541.4 1855.33   544.7 1855.15
  555.731855.369   564.3 1857.42  569.621857.423   587.2 1857.15  641.441859.487
  679.061859.891   793.6 1860.34   865.7  1861.9   944.3 1867.93  1098.2 1872.89
#Mann= 8 ,-1 , 0
       0     .12       0   69.18     .06       0  498.09     .12       0
   541.4    .045       0  555.73     .12       0  569.62     .06       0
  641.44     .08       0  679.06     .06       0
#XS Ineff= 2 , 0
                          733.13         1862.26
Permanent Ineff=
       F       F
Bank Sta=541.4,555.73
XS Rating Curve= 0 ,0
Exp/Cntr=0.3,0.1

Type RM Length L Ch R = 1 ,6555.2  ,354.2,351.1,346.1
XS GIS Cut Line= 3
      2088491.58      181830.324     2088154.975      182261.016
     2087784.241      182666.223
#Sta/Elev= 30
       0 2087.57    39.3  2065.1    91.6  2041.8   117.8  2034.3   137.5 2030.78
   176.8  2029.9   189.8 2026.57   202.9 2027.03   229.1 2021.14     275 2005.11
   308.91988.726  329.151977.687   376.4 1955.51   392.8 1946.41   405.9  1936.3
   415.7    1933   477.9 1887.39   507.4 1857.95   520.4 1854.33  554.211853.041
   556.4 1852.87     563 1852.72  570.131852.933   582.6 1855.67  598.671856.525
  622.761856.876   654.71857.094  866.071859.157  987.211863.819  1095.8 1867.51
#Mann= 11 ,-1 , 0
       0     .12       0   308.9    .016       0  329.15     .12       0
  554.21     .08       0   556.4    .045       0  570.13     .12       0
  598.67     .06       0  622.76    .016       0   654.7     .06       0
  866.07    .016       0  987.21     .06       0
#XS Ineff= 2 , 0
                          737.67         1860.58
Permanent Ineff=
       F       F
Bank Sta=556.4,570.13
XS Rating Curve= 0 ,0
Exp/Cntr=0.3,0.1

Type RM Length L Ch R = 1 ,6204.2  ,358.8,350,341.4
XS GIS Cut Line= 3
     2088157.264      181611.154     2087862.046      182070.379
     2087582.449      182539.809
#Sta/Elev= 30
       0 2017.64    22.9 2018.24      36 2017.11    52.3 2014.07    98.1 2002.93
   183.1 1980.58   228.8 1965.48   274.6 1960.49   313.8 1959.23   343.2 1954.65
   362.9 1949.95     389  1938.4   421.7 1925.92  442.151912.801   460.9 1898.95
  482.52 1880.64   500.2 1866.25   506.7 1859.09   513.2 1854.75   519.8 1853.15
  543.891850.439   545.9 1850.32   555.8 1850.38   568.8  1850.4   578.6 1852.83
  586.281852.854   614.6 1852.57   644.1 1854.12   850.2  1855.8  1092.3 1864.62
#Mann= 6 ,-1 , 0
       0     .12       0  442.15    .016       0  482.52     .12       0
  543.89    .045       0   555.8     .12       0  586.28     .06       0
#XS Ineff= 2 , 0
                          650.51         1857.64
Permanent Ineff=
       F       F
Bank Sta=543.89,555.8
XS Rating Curve= 0 ,0
Exp/Cntr=0.3,0.1