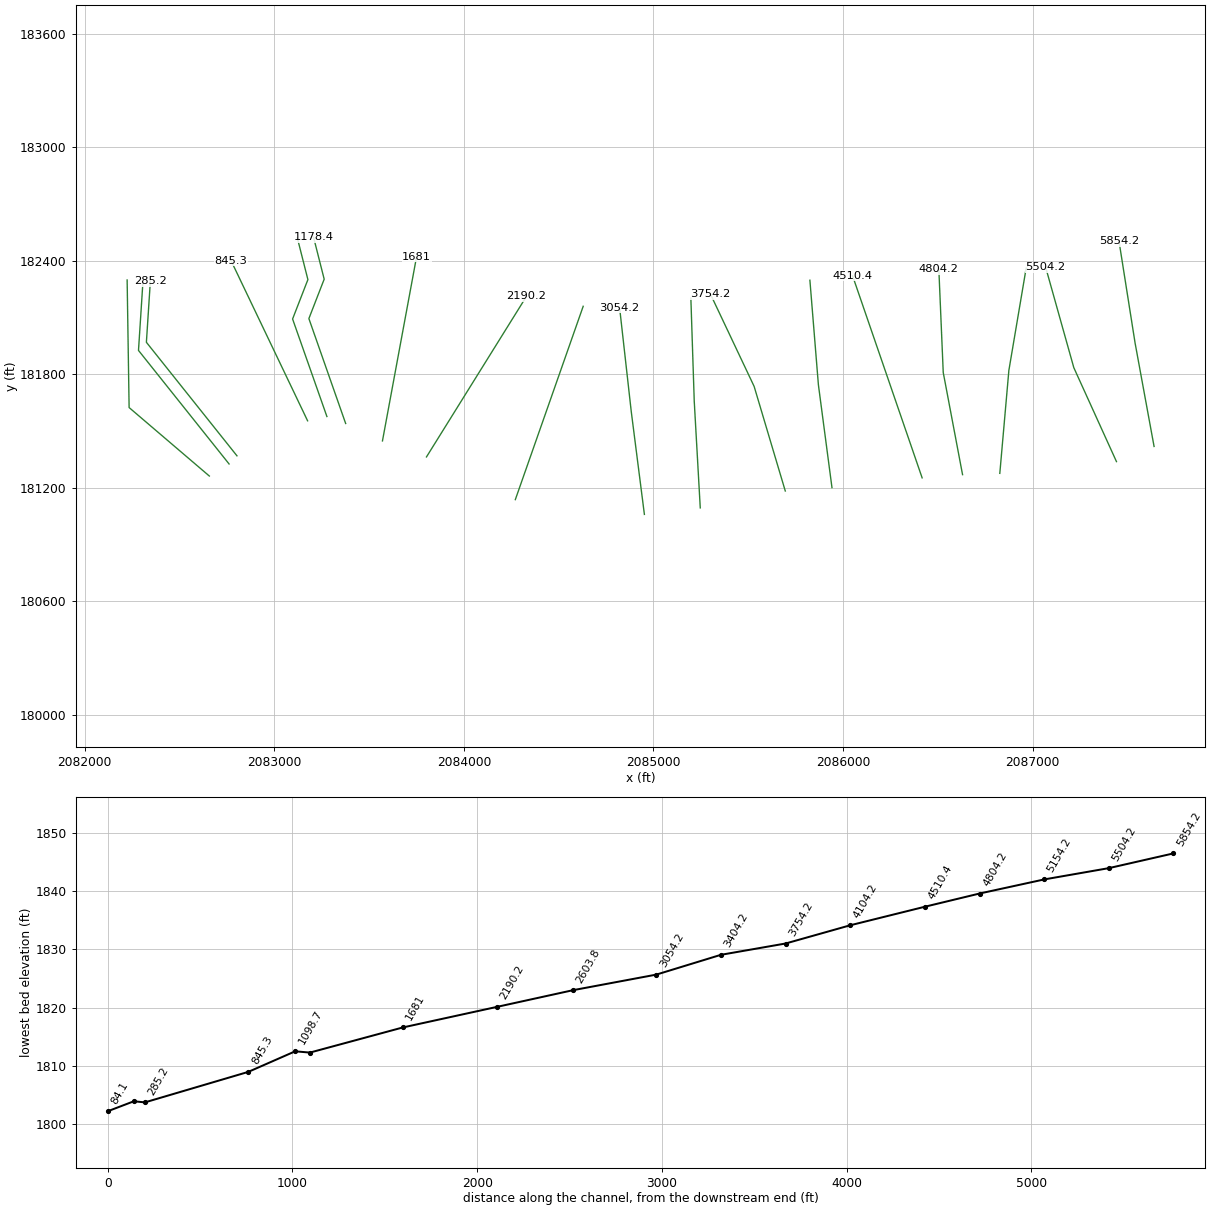
HEC-RAS study DRPLKCR.prj: DRPLKCR

--- DRPLKCR.g01 (geometry) --- (continued)

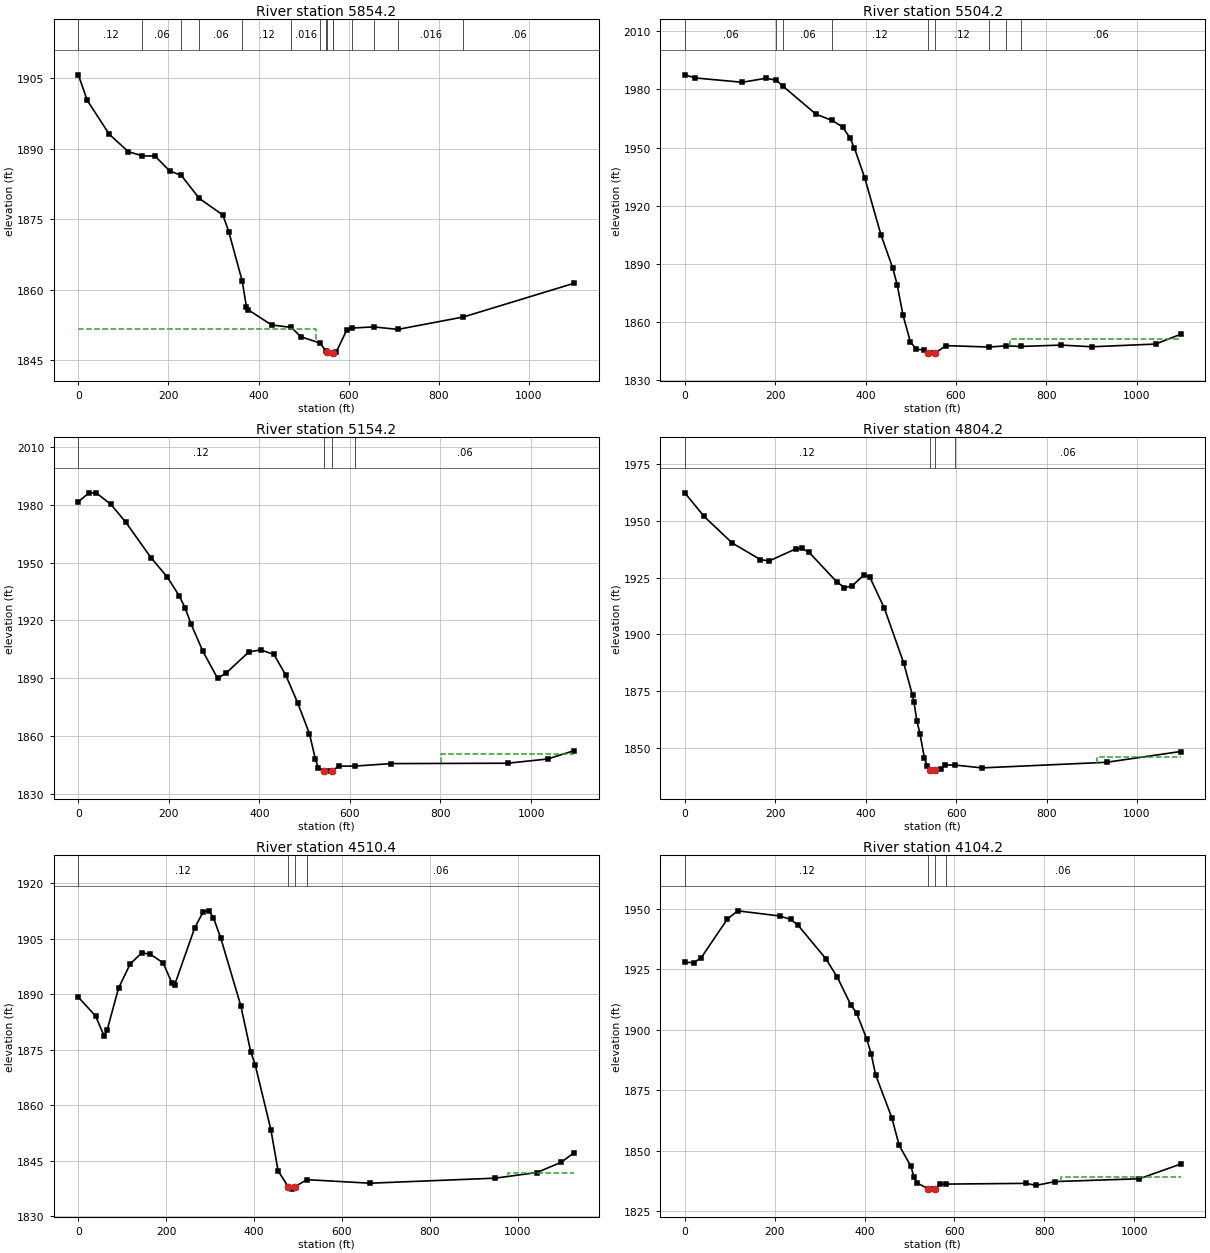
Type RM Length L Ch R = 1 ,5854.2  ,344.4,350,352.5
XS GIS Cut Line= 3
     2087641.376      181417.554     2087541.174      181964.738
     2087456.506      182502.122
#Sta/Elev= 30
       0 1905.68    19.6 1900.28    68.7 1893.02   111.3 1889.31  142.371888.449
   170.2 1888.39   202.9 1885.22  228.561884.274  268.451879.379   320.7 1875.86
   333.8 1872.32  363.581861.837     373 1856.37   376.3 1855.73   428.7 1852.47
  472.751851.934   494.1 1849.94  536.131848.618  549.631846.952   552.31846.609
   556.3 1846.47   566.1 1846.56  566.11 1846.56   572.7 1846.79   595.6 1851.37
   606.2  1851.8  655.591852.052  708.911851.518  854.49 1854.16  1100.3 1861.34
#Mann= 15 ,-1 , 0
       0     .12       0  142.37     .06       0  228.56     .12       0
  268.45     .06       0  363.58     .12       0  472.75    .016       0
  536.13     .12       0  549.63     .06       0   552.3    .045       0
   566.1     .06       0  566.11     .12       0   606.2    .016       0
  655.59     .06       0  708.91    .016       0  854.49     .06       0
#XS Ineff= 2 , 0
          526.59 1851.54
Permanent Ineff=
       F       F
Bank Sta=552.3,566.1
XS Rating Curve= 0 ,0
Exp/Cntr=0.3,0.1

Type RM Length L Ch R = 1 ,5504.2  ,361.5,350,340.1
XS GIS Cut Line= 3
     2087442.975      181337.519     2087218.047      181833.946
     2087069.151      182365.859
#Sta/Elev= 30
       0 1987.57    22.8 1985.96   127.3 1983.73   179.5  1985.8   201.81984.824
  217.771981.622   290.4 1967.23  325.98 1964.04   349.2 1960.69   365.5 1955.04
   375.3 1949.88   398.2  1934.4     434 1905.12   460.2 1887.86     470 1879.31
     483 1863.48   499.3 1849.78   512.4 1845.93   528.7  1845.6   538.5    1844
   541.7 1843.94   554.8 1844.01   577.7 1847.82  672.861847.087   710.41847.685
   744.31847.389   832.6 1848.09   901.3 1847.22  1041.8 1848.62  1097.4 1853.66
#Mann= 9 ,-1 , 0
       0     .06       0   201.8     .12       0  217.77     .06       0
  325.98     .12       0   538.5    .045       0   554.8     .12       0
  672.86     .06       0   710.4    .016       0   744.3     .06       0
#XS Ineff= 2 , 0
                          719.16         1850.98
Permanent Ineff=
       F       F
Bank Sta=538.5,554.8
XS Rating Curve= 0 ,0
Exp/Cntr=0.3,0.1

Type RM Length L Ch R = 1 ,5154.2  ,343.6,350,354.6
XS GIS Cut Line= 3
     2086827.543      181275.328     2086875.351       181819.83
     2086966.692      182360.873
#Sta/Elev= 30
       0 1981.47    22.9 1985.98    39.3 1986.11      72 1980.13   104.7  1970.9
   160.4 1952.57   196.4 1942.52   222.6 1932.89   235.7 1926.61   248.8  1918.3
   274.9 1904.15   307.7    1890   327.3 1892.94   376.4 1903.67   402.6 1904.79
     432 1902.44   458.2 1891.72   484.4 1877.45   510.6 1861.29   523.7  1848.2
   530.2 1843.56   543.3 1842.14   553.1    1842   559.7 1842.14     576 1844.57
  610.921844.601   690.3  1845.9   948.3 1846.09  1036.5 1848.28  1095.3  1852.6
#Mann= 4 ,-1 , 0
       0     .12       0   543.3    .045       0   559.7     .12       0
  610.92     .06       0
#XS Ineff= 2 , 0
                          801.24         1851.08
Permanent Ineff=
       F       F
Bank Sta=543.3,559.7
XS Rating Curve= 0 ,0
Exp/Cntr=0.3,0.1

Type RM Length L Ch R = 1 ,4804.2  ,290.1,293.8,300
XS GIS Cut Line= 3
     2086630.944      181268.588     2086529.084      181808.439
     2086505.843       182355.14
#Sta/Elev= 30
       0 1962.43    42.5 1952.05   104.6 1940.32   166.8 1932.99   186.4 1932.35
   245.3 1937.68   258.3 1937.93   274.7 1936.19   336.8 1922.96   353.2 1920.63
   369.5 1921.25   395.7  1926.1   408.8 1925.38   441.5 1911.43     484  1887.4
   503.6 1873.03   506.9 1869.98   513.4 1861.65     520 1856.19   529.8 1845.56
   536.3 1841.66   541.9 1839.98   549.4 1839.58  554.391840.029   565.8 1840.46
   575.6 1842.31     5981842.245   657.5 1841.01   932.7 1843.48  1096.6 1848.24
#Mann= 4 ,-1 , 0
       0     .12       0   541.9    .045       0  554.39     .12       0
     598     .06       0
#XS Ineff= 2 , 0
                          911.16         1845.72
Permanent Ineff=
       F       F
Bank Sta=541.9,554.39
XS Rating Curve= 0 ,0
Exp/Cntr=0.3,0.1

Type RM Length L Ch R = 1 ,4510.4  ,410.4,406.2,399.9
XS GIS Cut Line= 2
     2086417.735       181251.53     2086050.982      182319.239
#Sta/Elev= 30
       0 1889.17    39.3 1884.06    58.9 1878.65    65.4 1880.22    91.6 1891.61
   117.8 1898.08     144 1901.12   163.6 1900.78   193.1 1898.42   212.7  1893.1
   219.2 1892.45   265.1 1907.93   284.7 1912.28   297.8 1912.48   307.6 1910.59
     324 1905.24   369.8  1886.9   392.7 1874.34   402.5 1870.98   438.5 1853.32
   454.8 1842.27   477.8 1837.99   487.6 1837.33  492.791837.989  520.591839.886
   664.3 1838.93     949 1840.29  1043.9 1841.81  1099.5 1844.59  1128.9 1847.17
#Mann= 4 ,-1 , 0
       0     .12       0   477.8    .045       0  492.79     .12       0
  520.59     .06       0
#XS Ineff= 2 , 0
                          978.59         1841.69
Permanent Ineff=
       F       F
Bank Sta=477.8,492.79
XS Rating Curve= 0 ,0
Exp/Cntr=0.3,0.1

Type RM Length L Ch R = 1 ,4104.2  ,346.2,350,358.4
XS GIS Cut Line= 3
     2085942.071      181199.839     2085870.407      181743.906
     2085825.586      182296.429
#Sta/Elev= 30
       0  1927.8    19.6 1927.74    35.9 1929.56    94.7 1945.69   117.6  1949.1
   212.3 1946.94   235.2 1945.55   251.5 1943.25   313.6 1929.36   339.7 1921.56
   369.1 1910.32   382.2 1906.86     405 1896.03   414.8 1889.86   424.6 1881.31
   460.6 1863.61   476.9 1852.22     503 1843.57   509.6  1839.3   516.1 1836.72
   541.3 1834.32   545.5 1834.13   556.3  1834.3   568.4 1836.14     5801836.209
   758.7 1836.51   781.6 1835.69   824.3 1837.26  1011.3 1838.41  1103.1 1844.48
#Mann= 4 ,-1 , 0
       0     .12       0   541.3    .045       0   556.3     .12       0
     580     .06       0
#XS Ineff= 2 , 0
                           836.3         1838.95
Permanent Ineff=
       F       F
Bank Sta=541.3,556.3
XS Rating Curve= 0 ,0
Exp/Cntr=0.3,0.1

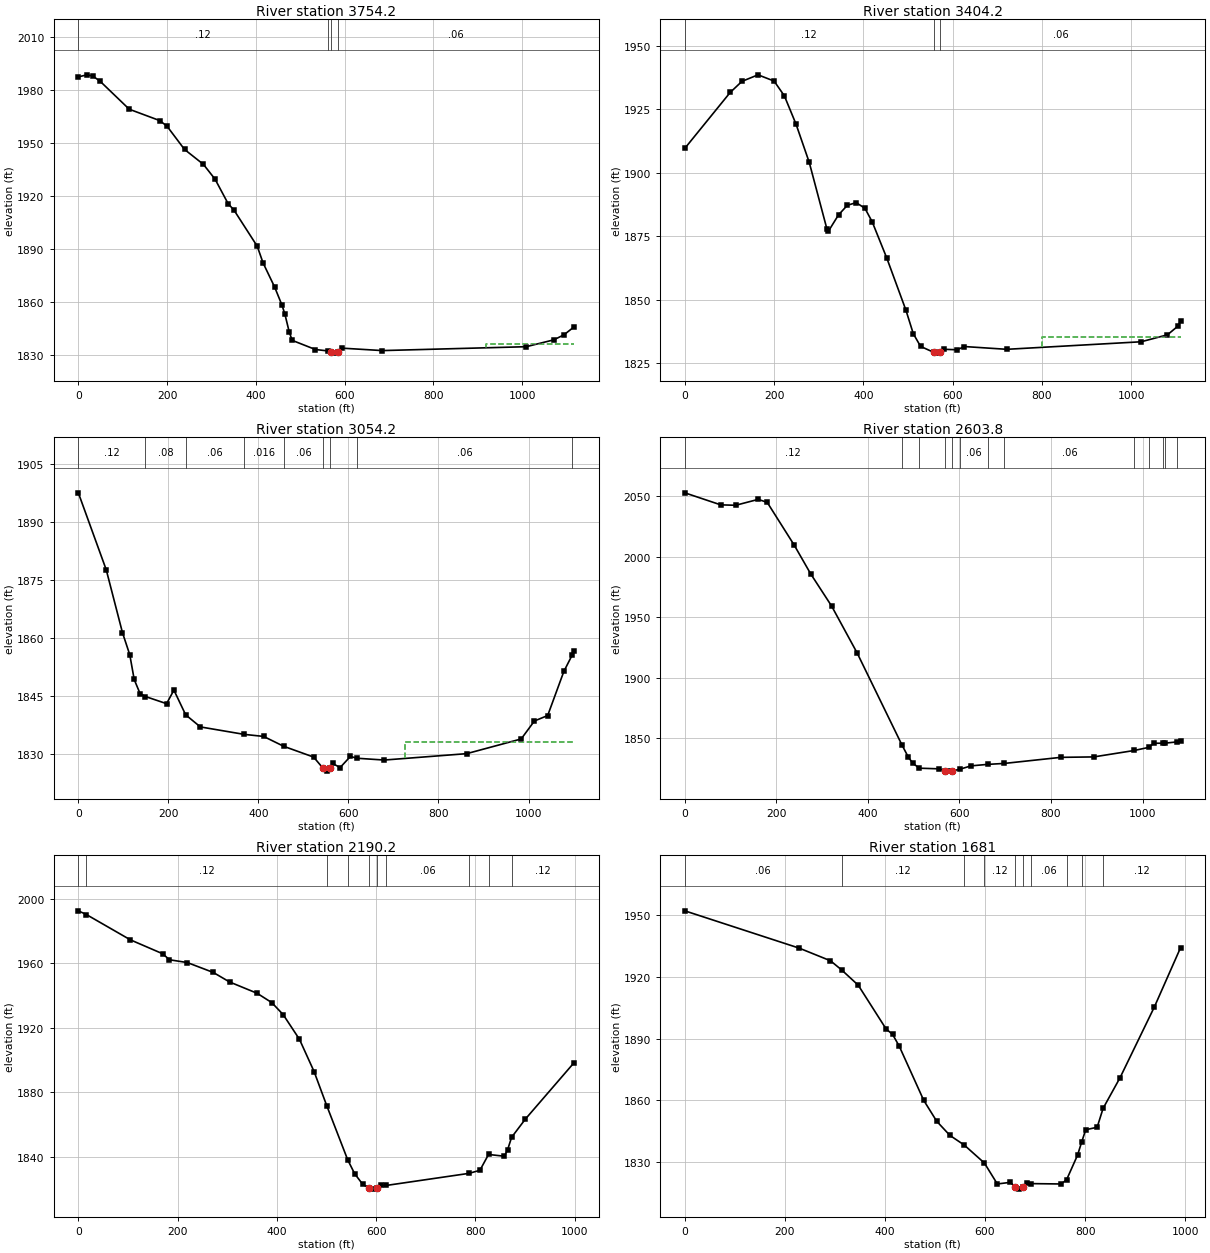
Type RM Length L Ch R = 1 ,3754.2  ,355.5,350,340.3
XS GIS Cut Line= 3
     2085695.746      181182.068     2085531.351       181735.11
     2085300.539      182223.889
#Sta/Elev= 30
       0 1987.64    19.7 1988.81    32.8  1988.1    49.2 1985.14   114.7 1969.31
   183.6 1962.85     200 1959.64   239.3 1946.51   281.9 1938.04   308.2 1929.62
   337.6 1915.76   350.8  1912.1   403.2 1891.62   416.3 1882.19   442.6 1868.37
   458.9 1858.25   465.5 1853.15   475.3 1843.02   481.9 1838.25   534.3 1833.05
  563.591832.218   570.4 1831.65   580.2    1831   584.5 1831.68   593.3 1833.84
   685.1 1832.44  1009.4 1834.64  1071.6 1838.53  1094.6 1841.39  1117.5 1845.93
#Mann= 4 ,-1 , 0
       0     .12       0  563.59     .06       0   570.4    .045       0
   584.5     .06       0
#XS Ineff= 2 , 0
                          919.54         1835.94
Permanent Ineff=
       F       F
Bank Sta=570.4,584.5
XS Rating Curve= 0 ,0
Exp/Cntr=0.3,0.1

Type RM Length L Ch R = 1 ,3404.2  ,348.2,350,351.6
XS GIS Cut Line= 3
     2085247.193      181092.776     2085215.461      181655.896
     2085197.587      182201.869
#Sta/Elev= 30
       0 1909.61   101.6  1931.6   127.9 1935.96     164 1938.54     200 1936.08
     223 1930.26   249.2 1919.08   278.7 1904.08   318.1 1877.99   321.4 1876.98
   344.3 1883.46     364 1887.22   383.7 1888.26   403.3 1886.06   419.7 1880.69
   452.5 1866.37   495.2 1845.94   511.6 1836.74   527.9 1831.72   557.5 1829.36
   567.3 1829.06  572.191829.389   580.4 1830.57   609.8 1830.38   626.2 1831.65
     721 1830.56    1022 1833.53  1080.8 1836.26  1103.7 1839.61  1110.3 1841.63
#Mann= 3 ,-1 , 0
       0     .12       0   557.5    .045       0  572.19     .06       0
#XS Ineff= 2 , 0
                          798.76         1835.41
Permanent Ineff=
       F       F
Bank Sta=557.5,572.19
XS Rating Curve= 0 ,0
Exp/Cntr=0.3,0.1

Type RM Length L Ch R = 1 ,3054.2  ,460.6,450.3,440
XS GIS Cut Line= 3
      2084952.42       181058.35     2084883.039      181602.641
     2084821.546      182151.946
#Sta/Elev= 30
       0 1897.49      62 1877.62      98 1861.42   114.3 1855.68   124.1 1849.31
   137.2 1845.65  149.121844.914     196 1843.07   212.3 1846.57  238.45 1840.19
   271.1 1837.07  368.281835.147   411.5 1834.62  456.361832.061   522.6 1829.29
  543.741826.385     552 1825.66  559.751826.433     565 1827.64   581.4 1826.57
   604.3 1829.44  619.52 1828.98   679.5 1828.52   862.7 1830.17   983.7 1833.96
  1013.1  1838.6  1042.6 1840.01  1078.5 1851.39 1096.791855.571  1101.4 1856.56
#Mann= 9 ,-1 , 0
       0     .12       0  149.12     .08       0  238.45     .06       0
  368.28    .016       0  456.36     .06       0  543.74    .045       0
  559.75     .12       0  619.52     .06       0 1096.79    .016       0
#XS Ineff= 2 , 0
                           725.7         1833.11
Permanent Ineff=
       F       F
Bank Sta=543.74,559.75
XS Rating Curve= 0 ,0
Exp/Cntr=0.3,0.1

Type RM Length L Ch R = 1 ,2603.8  ,418.7,413.6,407.6
XS GIS Cut Line= 2
     2084271.468      181136.513     2084629.541      182158.648
#Sta/Elev= 30
       0 2052.66    78.5 2042.73   111.2 2042.39   160.3 2047.25     180 2044.79
   238.9 2009.56   274.8 1985.89   320.7  1959.2   376.3  1920.6  473.961844.854
   487.5 1835.05   497.4 1829.73  512.091825.421   556.2 1824.87   569.3 1823.16
   572.6 1822.99  584.111823.161  601.081824.574     625 1827.33  661.191828.546
  698.251829.358   821.3 1834.36   893.3 1834.72  981.561840.021 1012.861842.542
  1024.1 1845.97 1044.161846.058 1048.211846.047 1075.461847.121    1083 1847.91
#Mann= 13 ,-1 , 0
       0     .12       0  473.96    .016       0  512.09     .12       0
   569.3    .045       0  584.11     .12       0  601.08     .06       0
  661.19    .016       0  698.25     .06       0  981.56     .12       0
 1012.86    .016       0 1044.16     .08       0 1048.21    .016       0
 1075.46     .12       0
Bank Sta=569.3,584.11
XS Rating Curve= 0 ,0
Exp/Cntr=0.3,0.1

Type RM Length L Ch R = 1 ,2190.2  ,500.6,509.3,517.5
XS GIS Cut Line= 2
     2083802.718      181362.207     2084330.061      182210.732
#Sta/Elev= 30
       0 1992.46   16.141990.177   104.8  1974.5   170.3 1965.82   183.4 1962.16
   219.5 1960.43   271.9  1954.3   304.6 1948.42   360.3 1941.39   389.8 1935.61
   412.7 1928.19   445.5 1912.91     475 1892.92  500.581871.739  542.841838.173
   556.8 1829.63   573.2 1823.01   586.3 1820.75   596.2 1820.11   602.7 1820.85
   609.2 1822.49  619.851822.363  786.961829.867   809.1 1831.76  826.531841.583
   858.2 1840.48   864.7 1844.29  872.98 1852.22   900.8 1863.52     999 1898.48
#Mann= 10 ,-1 , 0
       0     .06       0   16.14     .12       0  500.58    .016       0
  542.84     .12       0   586.3    .045       0   602.7     .12       0
  619.85     .06       0  786.96     .12       0  826.53    .016       0
  872.98     .12       0
Bank Sta=586.3,602.7
XS Rating Curve= 0 ,0
Exp/Cntr=0.3,0.1

Type RM Length L Ch R = 1 ,1681    ,506.6,502.5,498.3
XS GIS Cut Line= 2
     2083570.513      181446.843     2083750.634      182421.235
#Sta/Elev= 30
       0 1952.24   228.9 1934.03   291.1  1927.9  313.271923.466   346.6 1915.99
   402.2 1894.69   415.3 1891.98   428.4 1886.35   477.5 1859.85   503.6 1849.62
   529.8 1842.78  558.82    1838  598.731829.306   624.6 1819.09   650.8  1819.9
   660.6  1817.5   667.1 1816.58  675.291817.469   683.5 1819.33  691.071819.273
   752.2 1819.09  763.081821.198   784.9 1833.14  793.111839.525   801.2 1845.52
   824.1 1846.74  835.911855.929   869.9 1870.93   938.6 1905.47   990.9 1934.35
#Mann= 10 ,-1 , 0
       0     .06       0  313.27     .12       0  558.82    .016       0
  598.73     .12       0   660.6    .045       0  675.29     .12       0
  691.07     .06       0  763.08     .12       0  793.11    .016       0
  835.91     .12       0
Bank Sta=660.6,675.29
XS Rating Curve= 0 ,0
Exp/Cntr=0.3,0.1

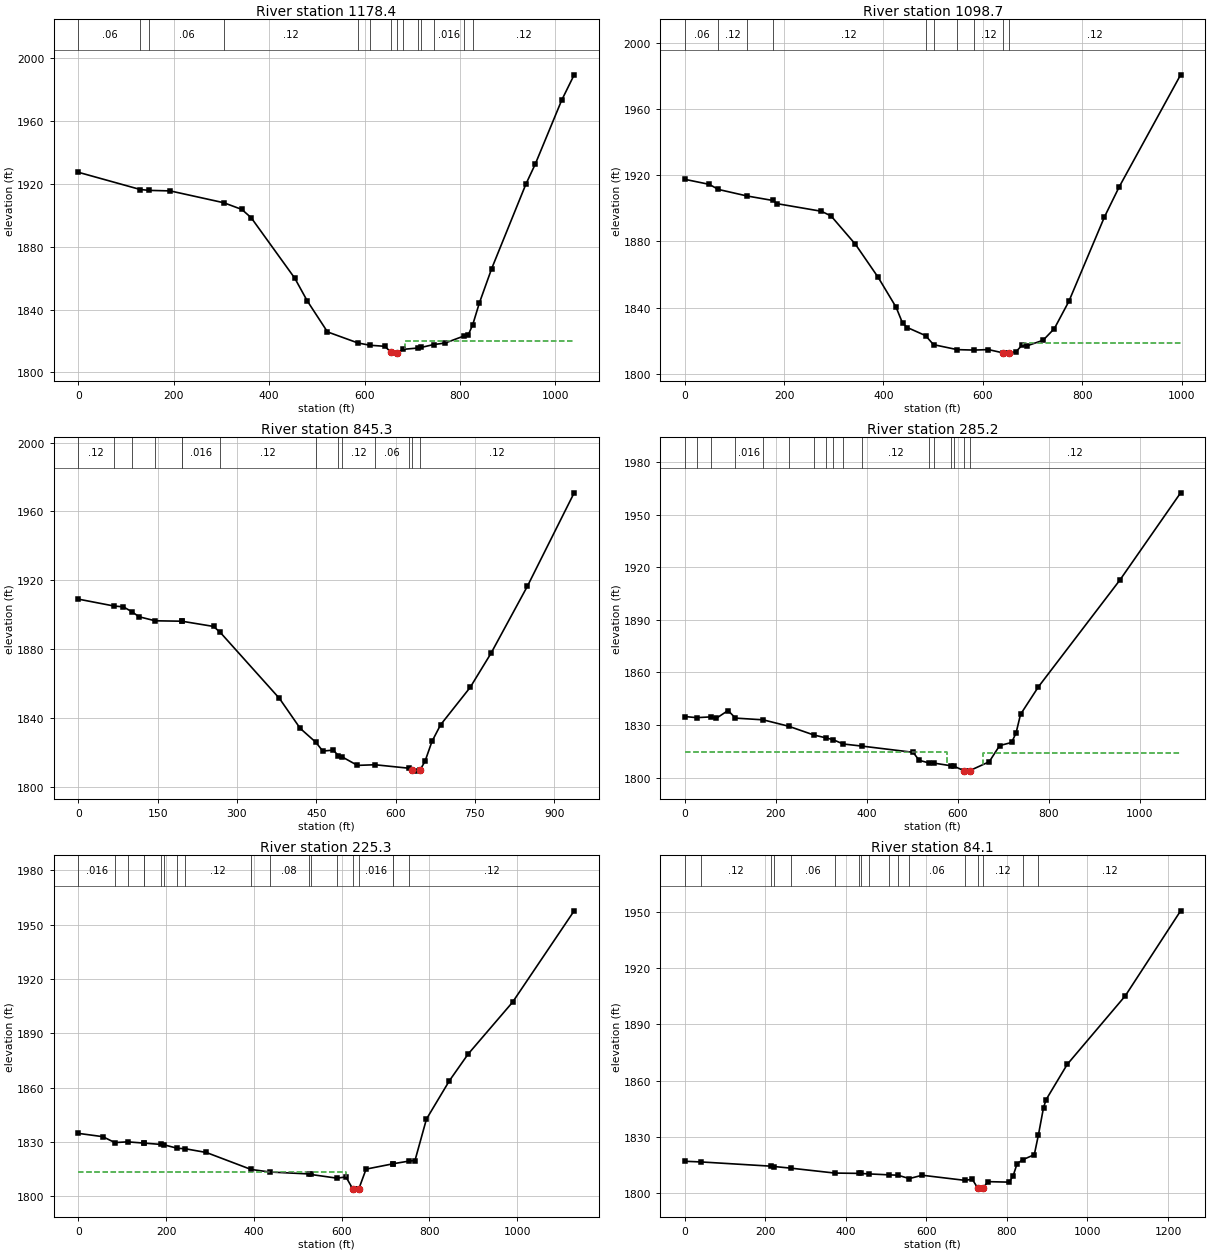
Type RM Length L Ch R = 1 ,1178.4  ,79.6,79.7,79.6
XS GIS Cut Line= 4
     2083376.347      181538.929     2083182.336      182093.616
     2083263.066      182301.949     2083207.076      182523.304
#Sta/Elev= 30
       0 1927.39  130.031916.404  149.09 1915.86   192.6 1915.53  304.761908.014
   342.8 1903.73   362.4 1898.44   453.8 1859.93   479.9 1845.51   522.3 1825.78
  586.261818.721  611.521817.284   642.7 1816.61   655.7 1812.69   662.1 1812.27
   668.6  1812.6  681.281814.693  712.961815.547  718.711815.899  744.641817.703
     769 1818.71     8081823.129   817.6 1824.04  826.711830.284   840.4 1843.93
   866.5 1866.09   938.3 1919.89   957.8 1932.54  1013.3  1973.3  1039.4 1989.42
#Mann= 14 ,-1 , 0
       0     .06       0  130.03     .12       0  149.09     .06       0
  304.76     .12       0  586.26     .06       0  611.52    .016       0
   655.7    .045       0   668.6     .12       0  681.28     .06       0
  712.96    .016       0  718.71     .12       0  744.64    .016       0
     808     .08       0  826.71     .12       0
#XS Ineff= 2 , 0
                          685.26            1820
Permanent Ineff=
       F       F
Bank Sta=655.7,668.6
XS Rating Curve= 0 ,0
Exp/Cntr=0.3,0.1

Type RM Length L Ch R = 1 ,1098.7  ,234.3,253.5,271.5
XS GIS Cut Line= 4
     2083277.389      181575.821     2083096.399      182091.446
     2083177.128      182299.779     2083121.139      182521.133
#Sta/Elev= 30
       0 1917.53    49.1  1914.5   67.811911.402  125.711907.442  176.681904.784
   186.5 1902.78   274.9 1898.23   294.5 1895.38   343.6 1878.23   389.4 1858.24
   425.4 1840.23   438.5 1830.54   448.3 1827.92  484.771823.067  500.711817.609
  548.551814.601  582.421814.329   611.2 1814.63   640.41812.655   643.6 1812.49
   653.3 1812.64   666.3 1813.15   679.2 1817.42   688.9  1816.9   721.3 1820.26
     744 1827.32   773.2 1843.78   844.9 1894.83   874.3 1912.84   998.2 1980.69
#Mann= 10 ,-1 , 0
       0     .06       0   67.81     .12       0  125.71     .06       0
  176.68     .12       0  484.77     .06       0  500.71    .016       0
  548.55     .06       0  582.42     .12       0   640.4    .045       0
   653.3     .12       0
#XS Ineff= 2 , 0
                          680.77         1818.76
Permanent Ineff=
       F       F
Bank Sta=640.4,653.3
XS Rating Curve= 0 ,0
Exp/Cntr=0.3,0.1

Type RM Length L Ch R = 1 ,845.3   ,554.7,560.1,565.2
XS GIS Cut Line= 2
     2083175.547      181553.179     2082771.902      182399.534
#Sta/Elev= 30
       0 1909.01   66.911905.031    85.2 1904.51  101.351901.657   114.8 1898.76
  145.331896.405   195.51896.166  195.861896.156   255.7 1893.12  268.391889.654
   380.3 1851.26   419.7  1833.8  449.261825.715   462.3 1820.62     482 1821.19
  491.751817.998  499.121817.196   527.9  1812.3  561.151812.673  624.681810.659
  630.921809.453     636 1808.96   645.9 1809.42   655.7  1814.7   668.8 1826.24
   685.2 1835.95     741 1857.64   780.3 1877.43   849.2 1916.48   937.7 1970.84
#Mann= 14 ,-1 , 0
       0     .12       0   66.91     .06       0  101.35     .12       0
  145.33    .016       0   195.5     .08       0  195.86    .016       0
  268.39     .12       0  449.26    .016       0  491.75     .08       0
  499.12     .12       0  561.15     .06       0  624.68     .12       0
  630.92    .045       0   645.9     .12       0
Bank Sta=630.92,645.9
XS Rating Curve= 0 ,0
Exp/Cntr=0.3,0.1

Type RM Length L Ch R = 1 ,285.2   ,60.1,59.9,59.9
XS GIS Cut Line= 3
     2082802.909      181368.008     2082325.045      181968.269
     2082345.878      182289.883
#Sta/Elev= 30
       0 1834.85   26.071834.222   57.38 1834.65    68.9  1833.8    95.1 1838.28
  111.311833.957  172.171832.974  228.031829.341   283.91824.297  310.661822.666
  326.621821.574  347.851819.205  390.421817.957   501.7 1814.44   514.8 1809.91
  535.931808.424  548.181808.269  585.941806.734  590.92 1806.57   613.1 1804.03
   616.4 1803.72   626.3 1804.02   668.9 1809.06   691.8 1818.29   718.1 1820.06
   727.9 1825.48   737.7 1836.08     777  1851.8   956.1 1912.71  1089.5 1962.44
#Mann= 17 ,-1 , 0
       0     .12       0   26.07     .08       0   57.38     .12       0
  111.31    .016       0  172.17     .06       0  228.03    .016       0
   283.9     .06       0  310.66    .016       0  326.62     .06       0
  347.85    .016       0  390.42     .12       0  535.93    .016       0
  548.18     .12       0  585.94     .06       0  590.92     .12       0
   613.1    .045       0   626.3     .12       0
#XS Ineff= 2 , 0
          575.45 1814.72  655.68          1814.1
Permanent Ineff=
       F       F
Bank Sta=613.1,626.3
XS Rating Curve= 0 ,0
Exp/Cntr=0.3,0.1

Type RM Length L Ch R = 1 ,225.3   ,155.9,141.2,126.1
XS GIS Cut Line= 3
     2082761.243       181325.04     2082283.378        181925.3
     2082306.816      182287.279
#Sta/Elev= 30
       0 1834.72    55.7  1832.9   83.151829.631  112.291830.028  148.891829.362
  149.721829.344   187.81828.615  196.321828.325  225.561826.488  243.751826.214
   291.8 1824.15  393.641814.784  436.041813.378  525.171812.304  529.631812.015
  589.551809.969   609.9 1810.65   625.4 1804.05   632.8 1803.91   639.4 1804.16
   655.8 1814.97  716.361817.865  718.051817.967  754.11 1819.42   767.2  1819.7
   793.4 1842.63   845.7 1863.82   888.2  1878.5   989.5 1907.16    1130 1957.69
#Mann= 19 ,-1 , 0
       0    .016       0   83.15     .12       0  112.29     .08       0
  148.89     .12       0  149.72     .08       0   187.8    .016       0
  196.32     .12       0  225.56     .08       0  243.75     .12       0
  393.64    .016       0  436.04     .08       0  525.17    .016       0
  529.63     .06       0  589.55    .016       0   625.4    .045       0
   639.4    .016       0  716.36     .08       0  718.05    .016       0
  754.11     .12       0
#XS Ineff= 2 , 0
          609.29 1813.51
Permanent Ineff=
       F       F
Bank Sta=625.4,639.4
XS Rating Curve= 0 ,0
Exp/Cntr=0.3,0.1

Type RM Length L Ch R = 1 ,84.1    ,93,84.1,74.6
XS GIS Cut Line= 3
     2082657.076      181261.238     2082233.899      181623.217
     2082223.482      182297.696
#Sta/Elev= 30
       0 1817.03   41.291816.664  213.381814.426  221.681814.244   263.51813.359
  372.541810.752  432.531810.578  438.311810.524  457.151810.303  505.921809.811
  529.161809.607  557.551807.818   589.6 1809.59  695.111806.886     714 1807.42
   727.2 1802.87   733.7  1802.2   740.2 1802.81   753.4 1806.18   805.7 1805.92
   815.6 1809.38   825.4 1815.84  839.891817.907     868 1820.54  878.261831.089
   890.9 1845.61   897.4 1849.87   949.8 1868.62  1093.9 1905.08  1231.4 1950.36
#Mann= 17 ,-1 , 0
       0     .06       0   41.29     .12       0  213.38     .06       0
  221.68     .12       0   263.5     .06       0  372.54     .12       0
  432.53     .08       0  438.31     .12       0  457.15     .06       0
  505.92    .016       0  529.16     .12       0  557.55     .06       0
  695.11     .12       0   727.2    .045       0   740.2     .12       0
  839.89    .016       0  878.26     .12       0
Bank Sta=727.2,740.2
XS Rating Curve= 0 ,0
Exp/Cntr=0.3,0.1

Chan Stop Cuts=-1
Use User Specified Reach Order=0
Composite Channel Slope=5